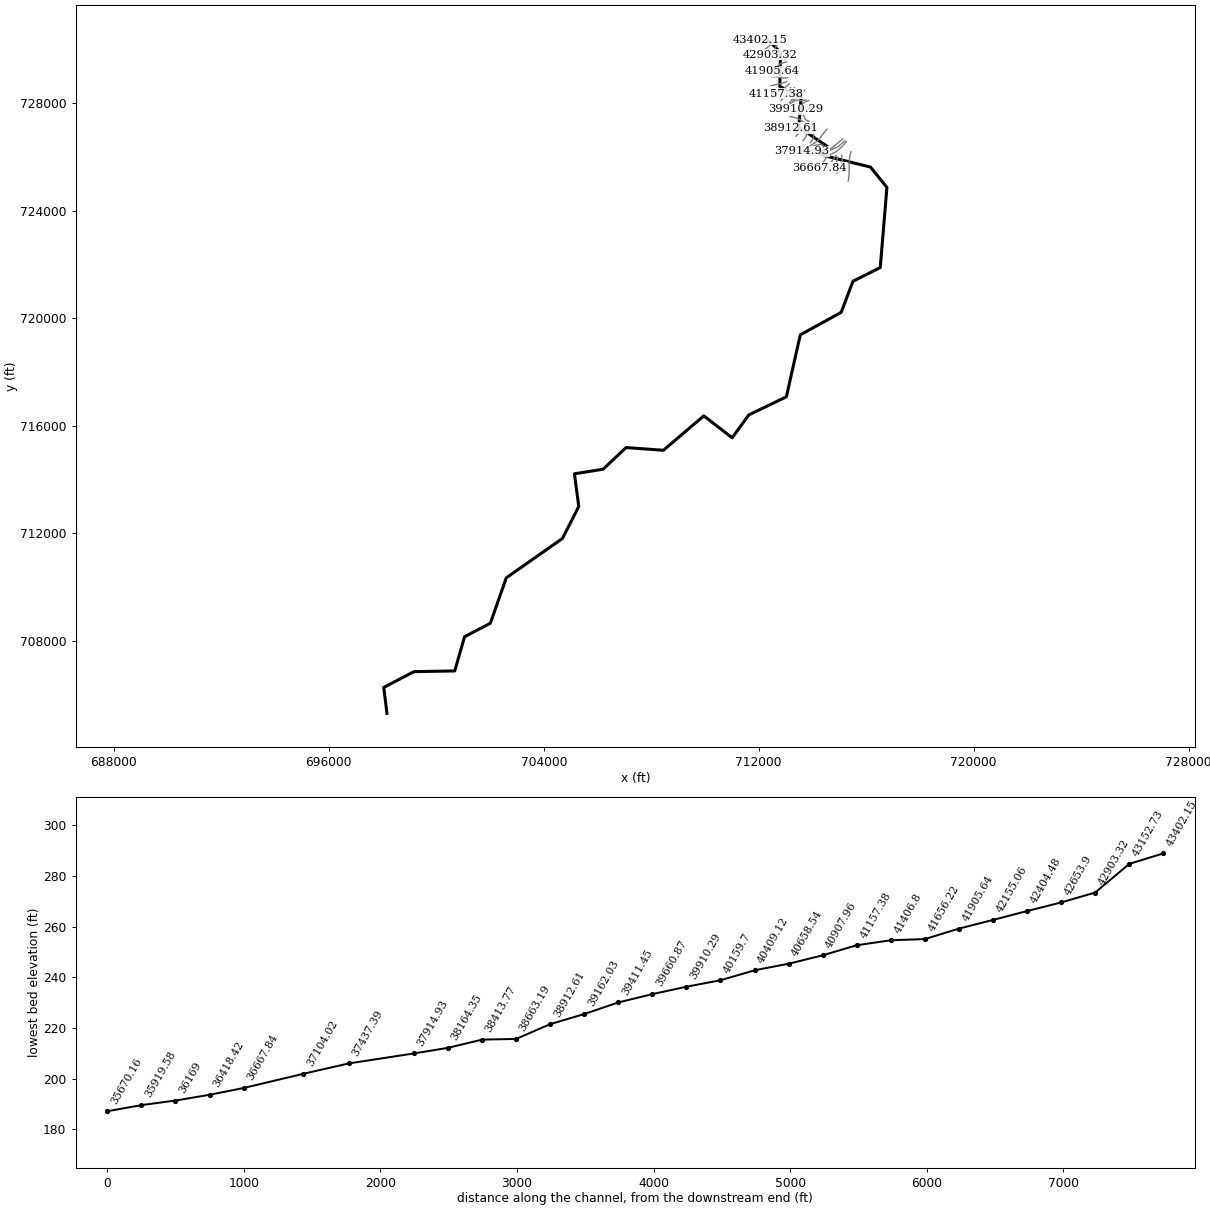
--- 4932_ras.prj (project) ---

Proj Title=4932
Current Plan=p01
Default Exp/Contr=0.3,0.1
English Units
Geom File=g01
Flow File=f01
Plan File=p01
Y Axis Title=Elevation
X Axis Title(PF)=Main Channel Distance
X Axis Title(XS)=Station
BEGIN DESCRIPTION:
RFD model 4932 exported to HEC-RAS
END DESCRIPTION:

--- 4932_ras.p01 (plan) ---

Plan Title=Plan 01
Program Version=4.10
Short Identifier=Plan 01
Geom File=g01
Flow File=f01
Subcritical Flow
Calc Critical at every XS
Secant Critical Depth

--- 4932_ras.f01 (steady flow) ---

Flow Title=Flow 01
Program Version=5.01
Number of Profiles= 6
Profile Names=10yr,25yr,50yr,100yr,100plus,500yr
River Rch & RM=4932,65,43402.15
 1546.17 2849.35 4226.63 5679.89 8292.6312108.25
River Rch & RM=4932,65,43152.73
 1883.05 3474.44  5158.9 6936.7410127.6414391.35
River Rch & RM=4932,65,42903.32
 1884.29  3477.1 5163.23 6943.02 10136.814404.65
River Rch & RM=4932,65, 42653.9
 1892.68  3495.2 5192.65 6985.6810199.0914494.94
River Rch & RM=4932,65,42404.48
 1895.05 3500.31 5200.98 6997.7710216.7414520.57
River Rch & RM=4932,65,42155.06
 1902.02 3515.41 5225.59 7033.5210268.9414596.48
River Rch & RM=4932,65,41905.64
 1903.14 3517.85 5229.57 7039.3210277.4114608.82
River Rch & RM=4932,65,41656.22
 1904.67 3521.17 5234.98 7047.1910288.8914625.57
River Rch & RM=4932,65, 41406.8
 1909.77 3532.22 5252.99 7073.3410327.0814681.03
River Rch & RM=4932,65,41157.38
 1911.78 3536.57 5260.09 7083.6810342.1814703.02
River Rch & RM=4932,65,40907.96
 1912.82 3538.83 5263.79 7089.0610350.0314714.45
River Rch & RM=4932,65,40658.54
 1913.78 3540.92  5267.2 7094.0210357.2714724.99
River Rch & RM=4932,65,40409.12
 1915.87 3545.44 5274.58 7104.7610372.9514747.83
River Rch & RM=4932,65,39910.29
 1917.95 3549.97 5281.97 7115.5110388.6414770.65
River Rch & RM=4932,65,39660.87
 1920.42 3555.34 5290.75 7128.29 10407.314797.85
River Rch & RM=4932,65,39411.45
 1922.72 3560.35 5298.94 7140.2210424.7214823.28
River Rch & RM=4932,65,39162.03
 2109.48 3945.73 5911.75 8013.6511699.9216585.84
River Rch & RM=4932,65,38912.61
 2110.74 3948.44 5916.17 8020.0611709.2916599.26
River Rch & RM=4932,65,38663.19
 2115.52 3958.76 5932.99 8044.52   1174516650.36
River Rch & RM=4932,65,38413.77
 2117.95    3964 5941.53 8056.9511763.1416676.31
River Rch & RM=4932,65,38164.35
 2128.03  3985.7 5976.86 8108.2811838.0916783.28
River Rch & RM=4932,65,37914.93
 2129.75 3989.41 5982.91 8117.0811850.9316801.64
River Rch & RM=4932,65,37437.39
 2132.72 3995.82 5993.35 8132.26 11873.116833.34
River Rch & RM=4932,65,37104.02
 2133.89 3998.35 5997.47 8138.2511881.8516845.84
River Rch & RM=4932,65,36667.84
 2206.74 4153.91 6249.76  8503.812415.5417600.22
River Rch & RM=4932,65,36418.42
 2207.99 4156.59 6254.11 8510.1212424.7817613.33
River Rch & RM=4932,65,   36169
 2208.84 4158.43  6257.1 8514.4712431.1317622.34
River Rch & RM=4932,65,35919.58
 2209.62  4160.1 6259.82 8518.4312436.9117630.52
River Rch & RM=4932,65,35670.16
 2210.96 4162.96 6264.47 8525.1712446.7517644.44
River Rch & RM=4932,65, 35199.6
 2218.22 4178.48 6289.66  8561.712500.0817719.67
River Rch & RM=4932,65,35098.28
 2218.54 4179.16 6290.76 8563.29 12502.417722.94
River Rch & RM=4932,65,34585.72
 2236.09 4216.61 6351.51 8651.3412630.9517903.96
River Rch & RM=4932,65,33795.24
34631.1250922.8359475.1282963.41109910.4120929.6
River Rch & RM=4932,65,32574.05
42340.0860236.8268123.5394791.92125580.9132401.7
River Rch & RM=4932,65,31535.46
42390.0960296.2768177.8894866.15125679.2132472.2
River Rch & RM=4932,65,30681.78
43780.4561944.7469680.5196918.38  128398134414.1
River Rch & RM=4932,65,29145.37
43853.6862031.3269759.2297025.87128540.4134515.5
River Rch & RM=4932,65,28418.34
43872.9862054.1469779.9597054.18128577.9134542.2
River Rch & RM=4932,65,27358.71
43954.68 62150.769867.7197173.99128736.6134655.1
River Rch & RM=4932,65,26329.05
44617.1962932.6470577.3498142.86130020.2135566.6
River Rch & RM=4932,65,25323.78
44693.7963022.9370659.1698254.56130168.2135671.5
River Rch & RM=4932,65,24198.32
45573.7864058.3571595.9899533.29131862.2136869.6
River Rch & RM=4932,65,22744.07
47043.2965780.13 73147.4101650.3134666.8138842.5
River Rch & RM=4932,65,21360.99
47113.4465862.0973221.06101750.8  134800138935.8
River Rch & RM=4932,65,19740.95
49806.0168993.5276022.26  105571  139861142461.8
River Rch & RM=4932,65,18350.36
50266.8969526.6976496.75106217.8  140718143054.8
River Rch & RM=4932,65,16963.73
50484.9169778.6376720.71106523.1141122.4143334.2
River Rch & RM=4932,65,16509.47
50592.9969903.4576831.63106674.3141322.7143472.5
River Rch & RM=4932,65,14945.76
50670.7469993.2376911.37  106783141466.7143571.9
River Rch & RM=4932,65,14349.82
51917.6671429.8678184.82108518.5143765.8145154.5
River Rch & RM=4932,65,13466.21
52350.5771927.3178624.62109117.7144559.7  145699
River Rch & RM=4932,65,12973.02
 52356.871934.4878630.94109126.3144571.2145706.9
River Rch & RM=4932,65,11677.28
53401.0973131.6579686.96  110565146477.1147010.3
River Rch & RM=4932,65,11330.88
53409.9773141.8179695.91110577.2146493.2147021.3
River Rch & RM=4932,65,10220.94
54036.4673858.16 80326.2111435.6147630.5147796.5
River Rch & RM=4932,65,8562.012
60081.1180702.3486290.91119553.9158385.6155035.3
River Rch & RM=4932,65,7223.833
60238.77 80879.3 86443.8119761.8158661.1155218.6
River Rch & RM=4932,65,5639.315
60501.4481173.9486698.25120107.9159119.6155523.5
River Rch & RM=4932,65,5354.434
60511.7281185.46 86708.2120121.4159137.5155535.4
River Rch & RM=4932,65,4861.146
60543.6381221.2486739.08120163.4159193.1155572.4
River Rch & RM=4932,65,4578.538
60580.4181262.4886774.68120211.8159257.3  155615
River Rch & RM=4932,65,2349.528
60809.3781519.0986996.09120512.9159656.2155879.9
River Rch & RM=4932,65,       0
67005.2788405.0292889.05128522.3  170267162851.7
Boundary for River Rch & Prof#=4932,65,1
Up Type= 0
Dn Type= 2
Boundary for River Rch & Prof#=4932,65,2
Up Type= 0
Dn Type= 2
Boundary for River Rch & Prof#=4932,65,2
Up Type= 0
Dn Type= 2
Boundary for River Rch & Prof#=4932,65,2
Up Type= 0
Dn Type= 2
Boundary for River Rch & Prof#=4932,65,2
Up Type= 0
Dn Type= 2
Boundary for River Rch & Prof#=4932,65,2
Up Type= 0
Dn Type= 2

--- 4932_ras.g01 (geometry) ---

Geom Title=4932
Program Version=4.10

River Reach=4932,65
Reach XY= 30
712349.302015662730364.137596264712812.322849035729893.825096264
712785.760349005728635.491762936713578.468682379728211.533429623
713495.135349035727113.095929623714568.572849035726390.700096264
714280.552015692726093.304262951716160.760349035725630.804262951
716772.913126826 724871.77648516716524.377247214721890.507496461
715509.099469423721379.396385357715070.210580528720223.146385357
713548.682802737719384.257496476713029.932802737717078.701940924
711629.238358289716403.007496461711013.960580498715552.313052028
 709957.01613611  716368.9797187708453.543913841715089.118607581
707064.655024976715189.118607581706211.877247185714383.563052028
705141.043913871  714212.7297187705303.543913871712996.757496461
704695.326321244711805.322311267702605.048543483710340.044533491
702012.687432349708651.850089043701050.881876796708146.294533506
700687.687432379706876.155644611699167.548543513706849.072311267
698044.631876826706261.572311282698164.163126826 705295.68689464

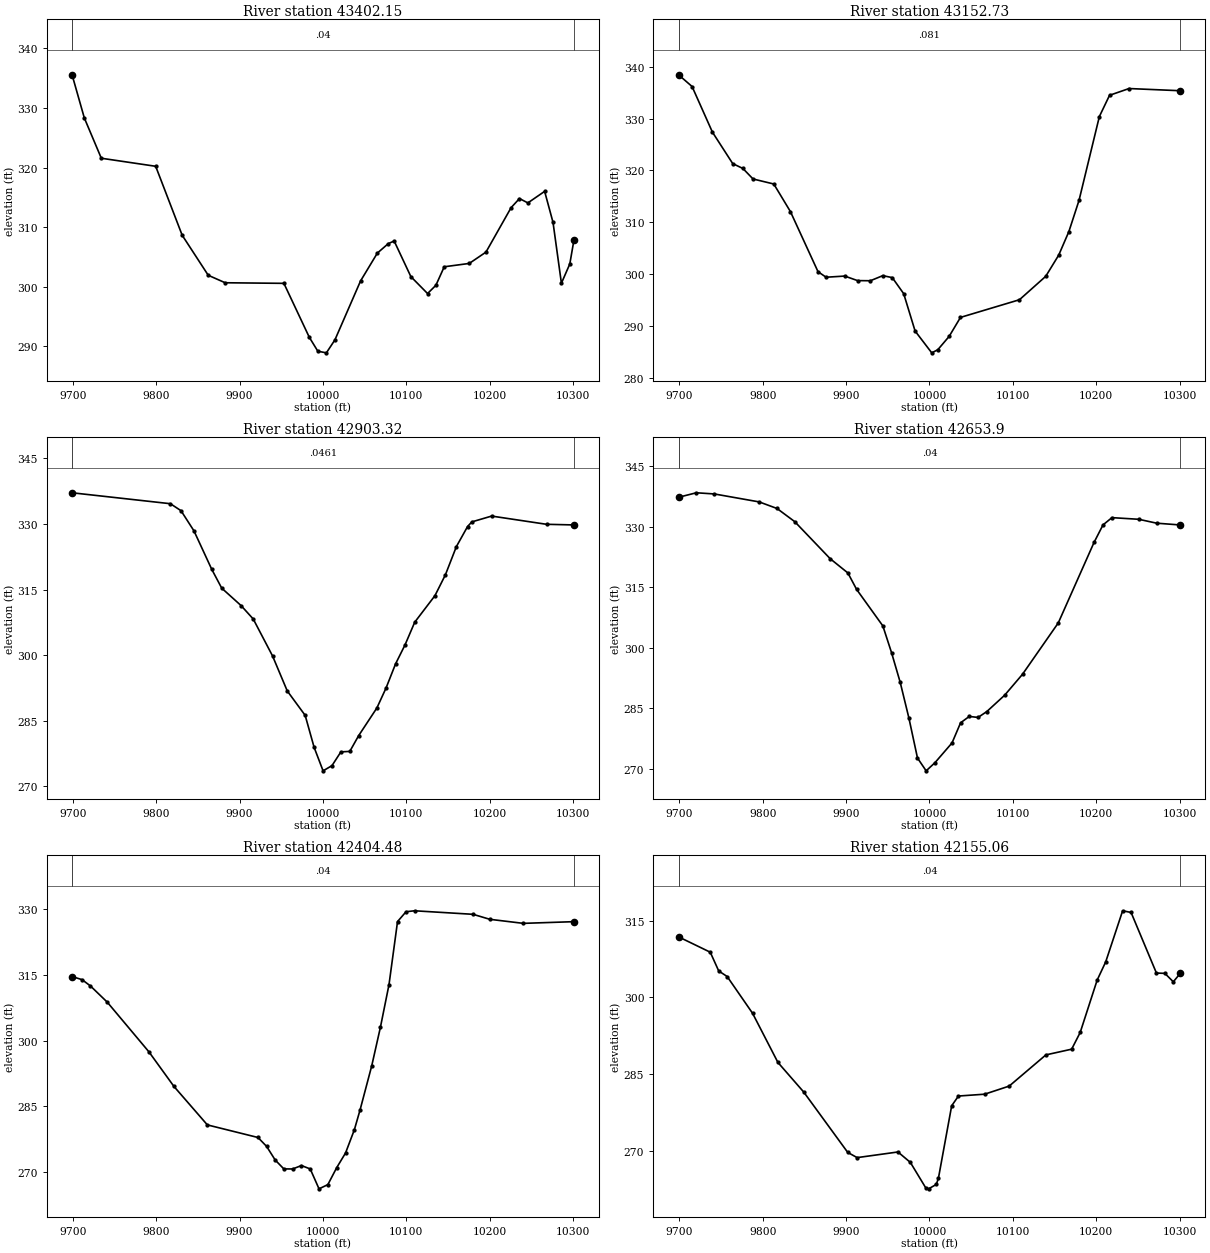
Type RM Length L Ch R = 1 ,43402.15,249.419100,249.419100,249.419100
XS GIS Cut Line= 6
712636.658190831730421.338258584712532.498976623730375.715721155
712444.600127693730354.381676667712389.689113566730354.895865428
 712238.90138211730379.644188836712050.152627104730367.380906847
#Sta/Elev= 30
9699.133335.56119713.847328.31359734.212321.56659799.406320.2178 9831.19308.6546
9862.457301.94149882.778300.68719953.183300.58879983.695291.53299993.897289.2061
10004.14288.936210014.39291.113110045.11300.987710065.29305.665810078.41307.2525
10085.42307.687610105.47301.715610125.48298.878910135.48300.263410145.48303.3667
 10175.5303.927310195.53305.826810225.66313.279310235.72314.807710245.78314.0764
10265.89316.012210275.95310.811910286.01300.609810296.07303.834410300.94307.7738
#Mann= 3 , 0 , 0
9699.133    0.04       09699.133    0.04       010300.94    0.04       0
#XS Ineff= 2 , 0
       0                10066.31       0
Bank Sta=9699.133,10300.94
Exp/Cntr=0.3,0.1

Type RM Length L Ch R = 1 ,43152.73,249.419100,249.419100,249.419100
XS GIS Cut Line= 6
712658.315719224730352.956873925712508.169908401730243.968909761
712366.457787179730115.234416127712312.095922973730070.608174942
712250.586964736730027.698428924712181.818033493729987.764519914
#Sta/Elev= 30
9699.025 338.4549715.261336.19019739.646327.39069764.032321.31139776.225320.3744
9788.417318.34499813.283317.37649833.223312.05579866.332300.45589876.023299.3869
9898.383299.60919913.757298.73469929.131298.70869944.024299.69039955.401299.3137
9969.093296.21759982.785289.007410002.75284.795510009.99285.391310023.61287.9636
10037.22291.634710107.97295.042810139.49299.561610155.07303.654310167.26308.1999
10179.45 314.22910203.84330.402310216.03334.493410239.44335.798810300.94335.3749
#Mann= 3 , 0 , 0
9699.025   0.081       09699.025   0.081       010300.94   0.081       0
#XS Ineff= 2 , 0
       0                               0
Bank Sta=9699.025,10300.94
Exp/Cntr=0.3,0.1

Type RM Length L Ch R = 1 ,42903.32,249.419200,249.419200,249.419200
XS GIS Cut Line= 6
712780.272812597730280.691871372 712660.94107977730140.906192134
 712585.48196285729967.561345016712549.991266646729909.565715069
712505.313906313729862.590985965712427.304773037729808.334353853
#Sta/Elev= 30
9699.054337.14999816.983334.64719829.702333.05039845.258328.42799866.562319.6341
9878.551 315.3149901.735311.32839916.342308.24969939.497299.79829957.151 291.779
9978.636286.18929989.378 278.86110000.12273.4871 10010.8  274.6810021.48277.8258
10032.16277.938610042.86281.568110064.67287.8873 10075.7292.471510087.07297.9811
10098.44302.334710110.05307.520710134.29313.591810146.87318.383110159.99324.8212
10173.41329.4202 10178.5330.4822 10202.3331.817410268.14 329.93310300.91329.7876
#Mann= 3 , 0 , 0
9699.054  0.0461       09699.054  0.0461       010300.91  0.0461       0
#XS Ineff= 2 , 0
       0                               0
Bank Sta=9699.054,10300.91
Exp/Cntr=0.3,0.1

Type RM Length L Ch R = 1 , 42653.9,249.419100,249.419100,249.419100
XS GIS Cut Line= 6
713094.819646468729996.437931268713001.693700821729958.990487876
712910.722472469 729925.98070549712859.765454992729909.919475398
712741.257989616729876.659114349712528.513606534729794.114191967
#Sta/Elev= 30
 9699.03337.25169720.392338.36489741.948338.07519795.839336.10259817.162334.4789
9838.438331.2201 9880.99322.04269902.178318.52629912.663314.45049944.118305.4263
9954.551298.80579964.928291.47019975.304282.69039985.681 272.7249996.057269.5615
10006.57271.564410027.11276.470610037.38281.4473 10047.8283.023510058.32282.7751
10068.84284.229710090.22288.271210111.67293.461310154.57306.166410197.48326.0871
10208.21 330.41210218.93332.213410251.11331.805710272.56330.840910300.97330.3998
#Mann= 3 , 0 , 0
 9699.03    0.04       0 9699.03    0.04       010300.97    0.04       0
#XS Ineff= 2 , 0
       0                               0
Bank Sta=9699.03,10300.97
Exp/Cntr=0.3,0.1

Type RM Length L Ch R = 1 ,42404.48,249.419100,249.419100,249.419100
XS GIS Cut Line= 6
713037.007997914729631.331850441712852.882599017729630.938300353
712671.298574154729682.928018409712604.174810573729694.041228008
712539.301385225729694.168095558 712445.26243721729680.084083501
#Sta/Elev= 30
9699.052 314.6129711.099313.89519721.132312.45489741.198308.77829791.232297.4298
9821.247 289.5369861.331280.75419922.055277.87989932.366275.85989942.677 272.745
9953.059270.71349963.614270.69729974.168271.47999984.723270.70239995.277266.1633
10005.88267.1287 10016.5 271.00410027.12274.358110037.68279.658910044.45284.1344
10058.51 294.24710068.93 303.05310079.22312.774210089.44327.154710099.65329.4022
10109.82 329.61910180.09328.8117 10200.1327.673110240.31326.748210300.95327.1337
#Mann= 3 , 0 , 0
9699.052    0.04       09699.052    0.04       010300.95    0.04       0
#XS Ineff= 2 , 0
       0                               0
Bank Sta=9699.052,10300.95
Exp/Cntr=0.3,0.1

Type RM Length L Ch R = 1 ,42155.06,249.419100,249.419100,249.419100
XS GIS Cut Line= 6
713032.498528032729538.171099202712833.296935689729493.344381743
712787.530503921729463.860998022712734.482629458 729400.29978222
712687.028346802729374.580526583712486.695258312729331.476987589
#Sta/Elev= 30
9699.141311.82589737.175308.82819747.318305.17269757.461304.0812 9787.89296.9207
9818.318287.32239849.206281.55889902.062269.76619913.323268.75249962.258 269.854
9977.113 267.8259995.934262.7617    9999262.6612 10008.3263.528210010.85264.7802
10026.68278.864810034.82280.7672 10066.2281.125310095.65282.707410139.68288.7948
10170.56289.909210180.79293.164410201.17303.394510211.37306.9287 10231.7316.9099
10241.83316.582810272.22 304.76210282.34   304.710292.47303.052610300.88304.7129
#Mann= 3 , 0 , 0
9699.141    0.04       09699.141    0.04       010300.88    0.04       0
#XS Ineff= 2 , 0
       0                               0
Bank Sta=9699.141,10300.88
Exp/Cntr=0.3,0.1

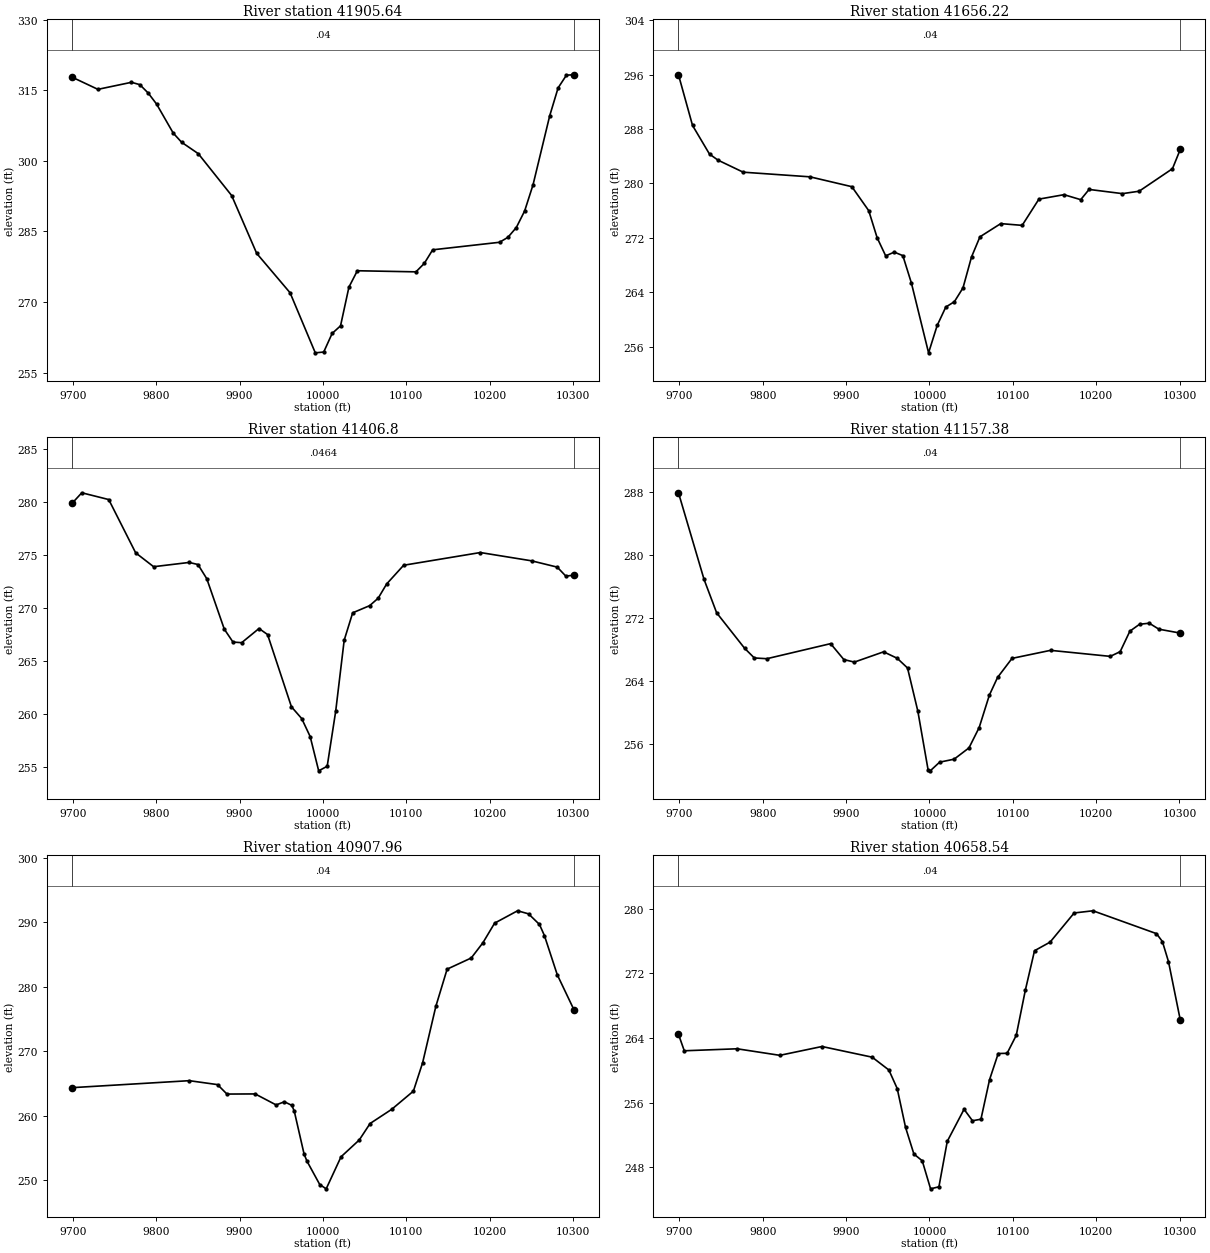
Type RM Length L Ch R = 1 ,41905.64,249.419100,249.419100,249.419100
XS GIS Cut Line= 6
   713095.826751729236.962467525713000.490501977 729227.19482658
712833.346901147729220.321333891712794.882006599729215.103183531
712741.416795728729208.145109788 712496.08572572729189.276291256
#Sta/Elev= 30
9699.059317.76199730.047315.17489770.256316.66859780.309316.17369790.361314.3892
9800.389312.05539820.406305.88279830.415303.94439850.431301.51769890.465292.6292
9920.491280.34729960.524271.98589990.773 259.23110000.88259.403310010.97263.3458
10021.05264.964810031.13273.191610041.22276.6607 10111.5 276.42610121.53278.2266
10131.56281.104310211.79282.704210221.82283.760810231.85285.825310241.88289.3577
10251.91294.890210271.97309.5892   10282315.483710292.03318.191110300.97318.2673
#Mann= 3 , 0 , 0
9699.059    0.04       09699.059    0.04       010300.97    0.04       0
#XS Ineff= 2 , 0
       0                               0
Bank Sta=9699.059,10300.97
Exp/Cntr=0.3,0.1

Type RM Length L Ch R = 1 ,41656.22,249.419100,249.419100,249.419100
XS GIS Cut Line= 6
 713081.58614355728960.081396201712987.577253435728945.843657721
712909.986083574728945.215631385712842.668064165728953.394149215
712671.455731684  728989.5885491712485.589055679728995.725574454
#Sta/Elev= 30
9699.063295.97429715.932288.52179736.273284.31319746.443283.42469776.678281.6522
9856.827280.96929906.993279.51969927.218276.00039937.331272.00789947.576269.3495
9957.862269.90059968.147269.38259978.433 265.3469999.004255.091210009.33259.1188
10019.65261.820810029.96262.611310040.28264.6373 10050.5269.183610060.62272.1499
10085.56274.091310111.25273.833510131.34277.691510161.42278.344810181.48277.6117
 10191.5279.116510231.51278.498810251.51278.853610291.51282.165510300.93285.0195
#Mann= 3 , 0 , 0
9699.063    0.04       09699.063    0.04       010300.93    0.04       0
#XS Ineff= 2 , 0
       0                               0
Bank Sta=9699.063,10300.93
Exp/Cntr=0.3,0.1

Type RM Length L Ch R = 1 , 41406.8,249.419200,249.419200,249.419200
XS GIS Cut Line= 6
713045.837519193728813.332539027712940.184415605728771.142931456
712884.401472265728751.849223606712838.148455222728738.257591543
712623.601714851728695.059689297712465.476549535728659.467417554
#Sta/Elev= 30
9699.033279.89569710.702280.89119743.006280.25059775.309275.21949796.845273.9091
9839.446274.31219850.027274.11729860.609272.77589881.622268.01129892.045266.7933
9902.468266.73449923.262268.07329933.524267.50219962.159  260.689974.473259.5683
9984.655257.86439994.837254.631910005.05255.064510015.24260.258510025.43266.9668
10035.61269.554310055.99270.231610066.18270.933610076.36272.278810096.74274.0463
10188.73275.247910250.23274.464910280.98273.870510291.23273.025210300.99273.1029
#Mann= 3 , 0 , 0
9699.033  0.0464       09699.033  0.0464       010300.99  0.0464       0
#XS Ineff= 2 , 0
       0                               0
Bank Sta=9699.033,10300.99
Exp/Cntr=0.3,0.1

Type RM Length L Ch R = 1 ,41157.38,249.419100,249.419100,249.419100
XS GIS Cut Line= 6
713134.275945594728725.393712337713014.565465829728619.101306522
712937.350299919 728556.56870184712778.214685197728443.631116983
712715.243297242728402.988785845712652.934279631728366.081401936
#Sta/Elev= 30
9699.024 287.946 9729.74276.94099744.801272.71429778.294268.21689789.985266.9836
 9805.04266.8873 9881.52268.79899897.409266.77579910.027266.45829945.077267.7609
9961.383266.94369973.762265.7126 9986.14260.23269998.519252.7368   10001252.6567
10012.26253.756510029.64254.135210047.49255.570310059.71258.151210071.94262.2665
10081.75264.506110099.12266.929410145.32267.948610216.95267.184410228.85267.7832
10240.47270.379410252.09271.258710263.72 271.39210275.34270.631710300.99270.1375
#Mann= 3 , 0 , 0
9699.024    0.04       09699.024    0.04       010300.99    0.04       0
#XS Ineff= 2 , 0
       0                               0
Bank Sta=9699.024,10300.99
Exp/Cntr=0.3,0.1

Type RM Length L Ch R = 1 ,40907.96,249.419100,249.419100,249.419100
XS GIS Cut Line= 6
713191.367058937728588.622365419713083.810749891728387.383640473
 713056.68176631728344.245211478712940.352993596728209.531104689
712890.598280979 728160.61318191712833.533911803728112.062675929
#Sta/Elev= 30
9699.067264.36479839.668265.44889873.525264.83789884.811263.37329918.668263.3926
9943.814261.68699953.706262.17689962.598261.62089965.519260.74549977.332 254.068
9980.799252.96229996.112249.338310003.84248.670110021.66253.643310043.53256.2531
10056.51258.805510082.47261.009910108.43263.827610119.51268.2362 10135.4276.9956
10148.88 282.74810177.79284.479610191.81286.842410205.84289.884610233.38291.8041
10246.51291.328610259.64289.681210265.56287.963610280.99281.879610300.96276.4614
#Mann= 3 , 0 , 0
9699.067    0.04       09699.067    0.04       010300.96    0.04       0
#XS Ineff= 2 , 0
       0                               0
Bank Sta=9699.067,10300.96
Exp/Cntr=0.3,0.1

Type RM Length L Ch R = 1 ,40658.54,249.419100,249.419100,249.419100
XS GIS Cut Line= 6
713329.484696951 728581.51835939713291.650588533728444.372382308
713282.072611582 728257.72032101 713270.36614707 728199.85485053
713231.320904013728127.598503362713145.145573371728029.534982669
#Sta/Elev= 30
9699.082264.45339706.052262.4197 9769.39262.66669820.597 261.8579871.162262.9485
9931.358261.62839951.361260.04489961.363257.75419971.365252.95119981.366249.6613
9991.368248.825410001.37 245.35810011.38245.610610021.39251.230210041.52255.1908
10051.62253.772210061.76253.961310072.13258.861710082.49 262.08110093.15262.1092
10104.11264.329710115.06269.936810126.02274.786110144.69275.848310173.53  279.45
10196.06279.721610272.26276.896210279.35275.920110286.66273.435810300.84266.2023
#Mann= 3 , 0 , 0
9699.082    0.04       09699.082    0.04       010300.84    0.04       0
#XS Ineff= 2 , 0
       0                               0
Bank Sta=9699.082,10300.84
Exp/Cntr=0.3,0.1

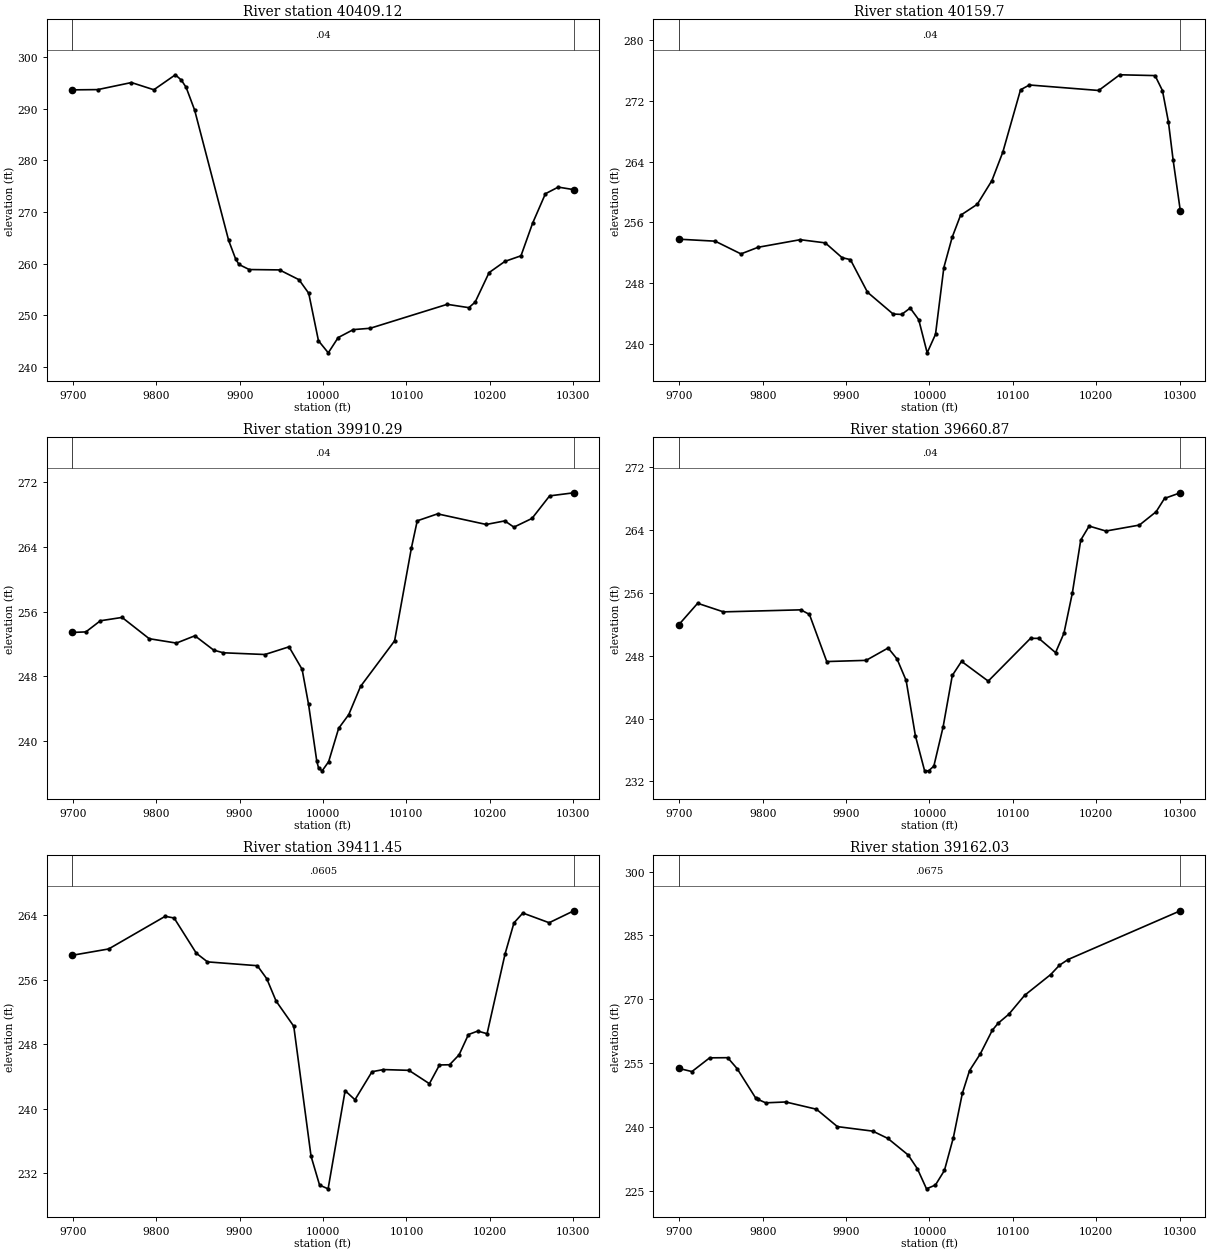
Type RM Length L Ch R = 1 ,40409.12,249.419100,249.419100,249.419100
XS GIS Cut Line= 6
713711.486117799728497.926605908713597.261434073728365.319403354
713511.718818127728236.830197108713445.599790613728224.939031707
713397.216694991728205.028920699713276.878122185728112.785481246
#Sta/Elev= 30
9699.046293.65549729.883293.70749770.234295.07179797.135293.6773 9822.94296.5753
9830.195295.52329835.838294.1386 9846.03289.74279886.839264.51089895.085260.9784
9899.167259.86369911.495258.8809 9947.83258.80969971.186256.91289982.864254.2892
9994.541245.0984 10006.3242.759510018.17 245.71310036.36247.256310056.57 247.514
10148.93252.148810174.89251.502910182.42252.570410199.17258.289510218.15260.4577
10237.42261.541510251.37267.856710266.72273.552310282.08274.835410300.83 274.342
#Mann= 3 , 0 , 0
9699.046    0.04       09699.046    0.04       010300.83    0.04       0
#XS Ineff= 2 , 0
       09855.537                       0
Bank Sta=9699.046,10300.83
Exp/Cntr=0.3,0.1

Type RM Length L Ch R = 1 , 40159.7,249.419200,249.419200,249.419200
XS GIS Cut Line= 6
 713746.85825029728129.765023166713595.360160659728096.761012949
713460.566403756728118.476666829713369.112720433 728113.71838657
713298.833223225728081.121607808713188.252755313727996.093692128
#Sta/Elev= 30
9699.144253.80259743.071253.53829774.009 251.8629794.565252.73489845.046 253.734
 9875.08253.31519895.168251.37339905.245251.10559925.727246.81229956.449243.9421
 9966.69243.88759976.931244.72939987.172243.19079997.283238.828410007.28241.2686
10017.28250.065910027.28254.060510037.28256.942710057.39258.402510074.92261.5222
10087.95 265.25510109.25273.4833 10119.9274.114310202.92 273.39110228.21275.4588
10270.54275.3521 10279.4273.379310286.56269.2552 10292.2264.235310300.84257.5323
#Mann= 3 , 0 , 0
9699.144    0.04       09699.144    0.04       010300.84    0.04       0
#XS Ineff= 2 , 0
       09835.261                       0
Bank Sta=9699.144,10300.84
Exp/Cntr=0.3,0.1

Type RM Length L Ch R = 1 ,39910.29,249.419100,249.419100,249.419100
XS GIS Cut Line= 6
713860.269321298728108.175117544713685.865425243728028.414501563
713643.258939819727993.374023034 713540.74240753727871.971541658
713457.687158266727820.039257984 713367.50258226727785.256167093
#Sta/Elev= 30
9699.074253.41589715.643253.48369733.006254.86269759.048255.27629791.602252.6414
9824.204252.09769846.399253.00319868.952251.22389880.504250.89679930.371250.6817
9959.278251.63479974.966248.84989982.679 244.521 9992.54237.49169994.791236.5937
    9999236.2721 10006.8237.405910018.78241.533310030.88243.232810045.04246.7262
 10085.9 252.37710106.08263.891810113.07267.244910137.42 268.10510195.76 266.792
10218.05267.2335   10229266.460410250.68267.539510271.83270.3335 10300.9270.7171
#Mann= 3 , 0 , 0
9699.074    0.04       09699.074    0.04       0 10300.9    0.04       0
#XS Ineff= 2 , 0
       0 9926.94                       0
Bank Sta=9699.074,10300.9
Exp/Cntr=0.3,0.1

Type RM Length L Ch R = 1 ,39660.87,249.419100,249.419100,249.419100
XS GIS Cut Line= 6
713977.226410728727822.422676008713765.549252767727767.182818275
713648.585958781 727716.08342814713608.158300337727703.889199011
713555.354357837727700.457253552713396.069442531727715.931591535
#Sta/Elev= 30
9699.035251.90519721.956 254.6729752.893253.58019845.705253.83959856.028 253.257
9876.816247.25749924.038247.41029950.447248.98399961.126247.58669972.035244.8485
9983.114 237.8289994.193233.3536    9999233.350910005.27233.952210016.34238.9171
 10027.4245.487410038.47247.282710070.48244.768610121.21  250.2110131.21250.2082
10151.27248.390910161.33250.868510171.39255.975110181.45262.713210191.51264.4978
10211.63263.866510251.86264.625810271.91266.322910281.94268.016410300.91268.7345
#Mann= 3 , 0 , 0
9699.035    0.04       09699.035    0.04       010300.91    0.04       0
#XS Ineff= 2 , 0
       09945.411                       0
Bank Sta=9699.035,10300.91
Exp/Cntr=0.3,0.1

Type RM Length L Ch R = 1 ,39411.45,249.419100,249.419100,249.419100
XS GIS Cut Line= 6
713877.831993568727336.517026453713795.458011304727361.843376898
713731.247532248727410.395482702713662.542763725727572.823469942
713622.880601324727617.963978129713446.263059229727696.240113796
#Sta/Elev= 30
9699.254259.03399743.108259.82279810.877263.87459821.585263.66229848.197259.2911
9861.588258.22029921.334257.74589932.625256.13189943.829253.35379965.002250.2314
9985.705234.10999995.946230.517610006.16230.057310026.56242.234110038.37241.1137
10058.81244.592410072.49244.855910103.05244.762110127.58243.105610139.67245.4277
10151.76245.454110163.17246.687110174.35249.201510185.54 249.63610196.72 249.306
10218.31259.217610228.95263.060910239.59 264.28110271.12263.077510300.74264.5604
#Mann= 3 , 0 , 0
9699.254  0.0605       09699.254  0.0605       010300.74  0.0605       0
#XS Ineff= 2 , 0
       0                               0
Bank Sta=9699.254,10300.74
Exp/Cntr=0.3,0.1

Type RM Length L Ch R = 1 ,39162.03,249.419100,249.419100,249.419100
XS GIS Cut Line= 6
713720.096495205727286.876588366713632.848657408727324.249954385
713515.130425656727409.594527805713468.858587159727434.631093543
713308.828945272727491.488997916713171.418216232 727507.11509971
#Sta/Elev= 30
9699.113253.79149715.165253.0286 9736.43256.25449758.068256.28879769.313253.7394
9791.803246.76429794.223246.50659803.643245.6873 9827.65245.88599864.513244.1829
9889.626240.09929932.093239.03449950.136237.32639974.551233.42839985.592230.1923
 9996.51225.480710007.24226.383110017.99 229.80210028.74237.530610039.49 247.923
10048.12253.256610060.98257.162910075.38262.728710082.48264.3965 10095.3266.5061
10114.16 270.93610145.47275.824610155.91278.002710166.26279.349110300.92290.8005
#Mann= 3 , 0 , 0
9699.113  0.0675       09699.113  0.0675       010300.92  0.0675       0
#XS Ineff= 2 , 0
       0                               0
Bank Sta=9699.113,10300.92
Exp/Cntr=0.3,0.1

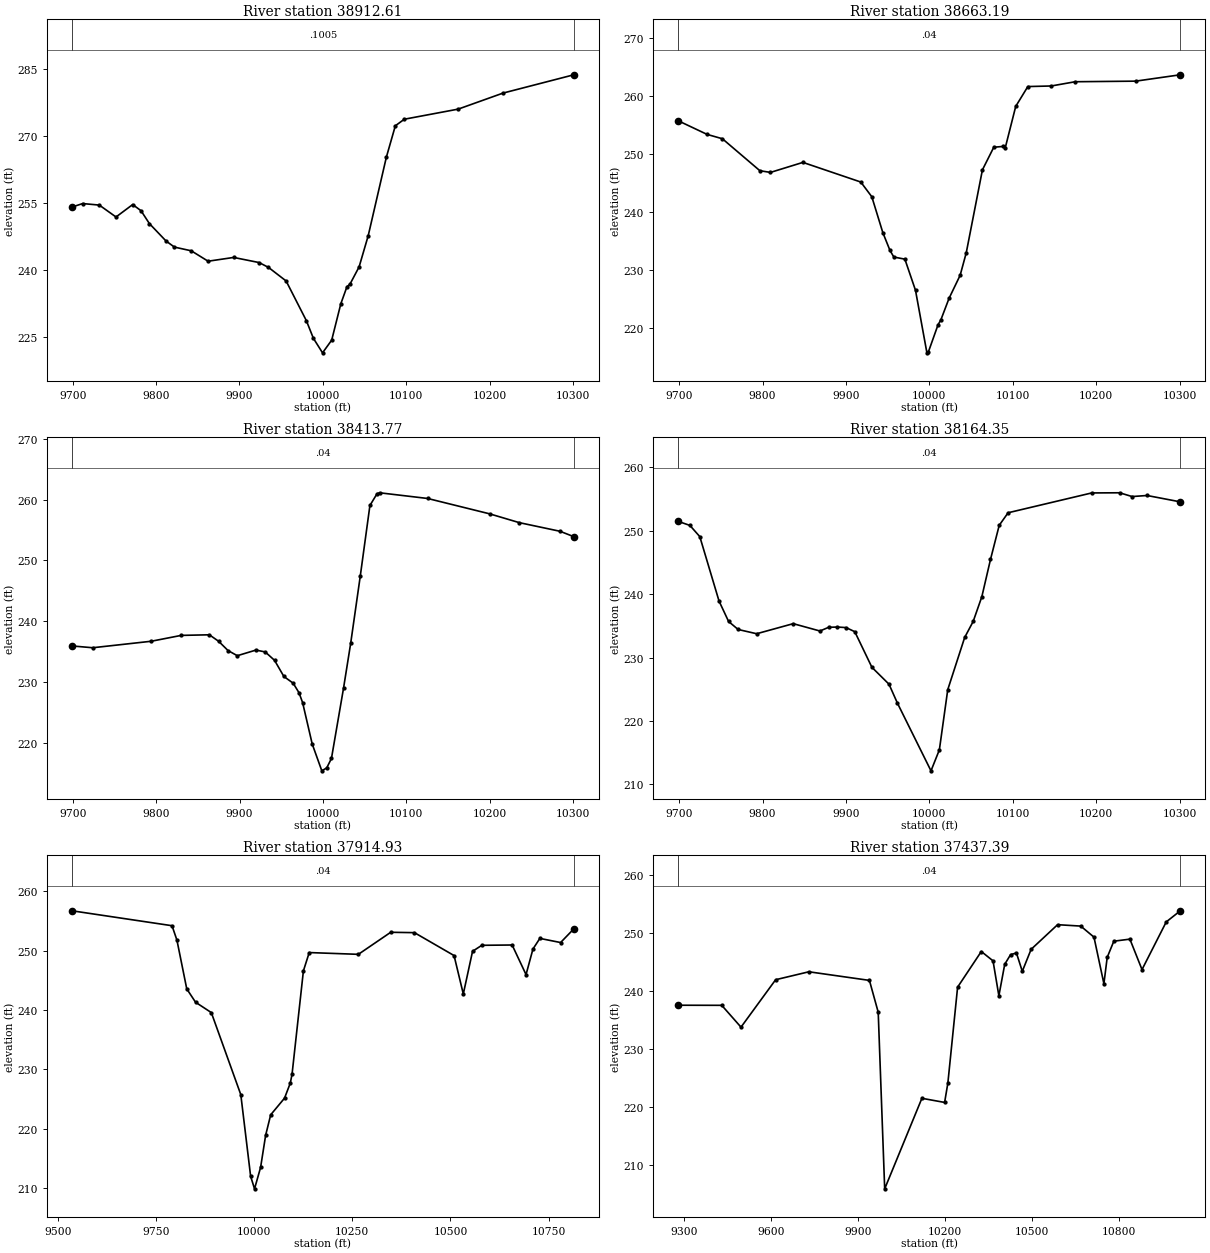
Type RM Length L Ch R = 1 ,38912.61,249.419100,249.419100,249.419100
XS GIS Cut Line= 6
713747.814555385727249.289406039713617.244301887727244.046342561
 713536.37348426727228.696962018713489.087946464727212.431969503
713393.467365063 727169.39002824713176.071382654727082.926240887
#Sta/Elev= 30
9699.061254.04189711.881254.83279731.888254.49149751.895251.83199771.903254.6109
9781.906253.2319 9791.91250.36469811.961246.45559821.989245.1034 9842.14244.2781
9862.351241.95159893.019242.79499923.526241.65039934.763 240.5689955.913237.5361
9980.185228.67149988.606224.7292 9999.59221.479610010.57 224.31510021.52232.4461
10028.82236.229610032.48236.818710043.44240.684910054.39247.668610076.14265.2012
 10086.9272.210110097.66273.675710162.23275.931410216.04279.515210300.99283.6069
#Mann= 3 , 0 , 0
9699.061  0.1005       09699.061  0.1005       010300.99  0.1005       0
#XS Ineff= 2 , 0
       0                               0
Bank Sta=9699.061,10300.99
Exp/Cntr=0.3,0.1

Type RM Length L Ch R = 1 ,38663.19,249.419200,249.419200,249.419200
XS GIS Cut Line= 6
713816.666131023727192.146666482713753.141366258727152.999163314
713698.296418039727107.318619296713651.593049674727059.264850886
713509.233122385726898.597946716713382.569971542726779.135658215
#Sta/Elev= 30
9699.046255.69459733.465253.35549751.757252.60859796.762247.0878 9809.47246.7976
9848.357248.52559917.771245.13469930.988242.59379944.205236.39969952.803233.3183
9957.422232.18699970.639231.8232 9983.39 226.4419997.073215.65279998.683215.7476
10010.37220.479610013.84221.356810023.65225.073410036.94229.045910044.24232.9182
10063.64247.235910077.26251.139810088.85251.285810090.87250.953910103.59258.1946
 10118.1261.615610146.16261.715210174.96262.448310247.39262.548510300.98263.6487
#Mann= 3 , 0 , 0
9699.046    0.04       09699.046    0.04       010300.98    0.04       0
#XS Ineff= 2 , 0
       0                               0
Bank Sta=9699.046,10300.98
Exp/Cntr=0.3,0.1

Type RM Length L Ch R = 1 ,38413.77,249.419100,249.419100,249.419100
XS GIS Cut Line= 6
713955.722440768727125.012420633713901.996843589727046.590461779
 713821.57573115726888.773887846713733.763673759726735.745617618
713687.558114286726666.073366866713644.857184752726611.111093403
#Sta/Elev= 30
9699.038235.93039723.944235.63369794.177236.70239830.063237.66689863.827237.7647
9874.998236.69049886.169235.1777 9897.34234.32259919.682235.24949930.854234.9403
9942.025233.55929953.196230.90479964.367229.79299971.322228.2334 9975.67226.6013
9987.189219.78519998.709215.371510004.63215.868910010.26217.411510024.72228.9615
10033.32236.363110044.82247.434110056.38259.049810064.91260.980210067.91261.1409
10125.56260.2048 10199.8257.680610235.53 256.22510284.42254.802810300.96253.9132
#Mann= 3 , 0 , 0
9699.038    0.04       09699.038    0.04       010300.96    0.04       0
#XS Ineff= 2 , 0
       0                               0
Bank Sta=9699.038,10300.96
Exp/Cntr=0.3,0.1

Type RM Length L Ch R = 1 ,38164.35,249.419100,249.419100,249.419100
XS GIS Cut Line= 6
 714149.06893116727086.579770204714072.353562108726930.881145009
714040.127819881726757.422059128714019.571985349726694.162045472
 713977.99774468726615.368387946713918.985109233726540.871611747
#Sta/Elev= 30
9699.055251.47529712.817250.84739724.702249.07839747.773238.91179759.227235.6915
9770.681234.42729792.896233.75729836.739235.34679868.731234.18989879.259234.7744
9889.691234.81359900.124234.72699910.556234.0783 9931.09228.46029951.562225.7969
 9961.67222.809910001.93212.126510011.97215.436210022.02224.929110042.32233.1712
10052.54235.706110062.91239.603610073.28245.477410083.75250.8653 10094.4252.8443
10194.65255.970810228.14255.9965 10243.1255.400410261.02255.567310300.91254.5632
#Mann= 3 , 0 , 0
9699.055    0.04       09699.055    0.04       010300.91    0.04       0
#XS Ineff= 2 , 0
       0                               0
Bank Sta=9699.055,10300.91
Exp/Cntr=0.3,0.1

Type RM Length L Ch R = 1 ,37914.93,477.547600,477.547600,477.547600
XS GIS Cut Line= 6
714544.208625639727040.519789356714408.724022478726881.841577485
714229.342900127726645.461568236714159.821215272726574.611074343
713779.512087584726343.842075005713590.887683451726215.830965325
#Sta/Elev= 30
9536.045256.68859790.864254.17659803.376251.75179828.398243.55269850.807241.3051
9890.955 239.5649966.023225.76519991.072212.0296   10001209.918110016.45213.5267
10029.31218.937410042.15222.370410077.41225.173910092.15227.720710096.59229.2272
10125.44246.577910140.29249.660510265.42249.361810347.77253.071210408.22253.0091
 10509.1249.155510532.64242.697110556.18249.870210579.72250.880810656.97250.9337
10692.41245.955710710.01250.255310727.61252.043410780.42251.346410814.16253.6549
#Mann= 3 , 0 , 0
9536.045    0.04       09536.045    0.04       010814.16    0.04       0
#XS Ineff= 2 , 0
       0                               0
Bank Sta=9536.045,10814.16
Exp/Cntr=0.3,0.1

Type RM Length L Ch R = 1 ,37437.39,333.364300,333.364300,333.364300
XS GIS Cut Line= 6
715132.912761241726678.864533539714693.970037639 726320.76410687
  714565.4978154726338.125217974714325.914482117726470.069662437
714086.331148773726438.819662437713636.274775922726187.979794949
#Sta/Elev= 30
9281.871237.56919431.164237.5525 9497.45233.79429616.765  241.969731.263243.3268
 9939.83 241.8459970.103236.36989992.411 205.96210120.59221.548510198.85220.8363
10210.03224.166610243.57240.677810325.25246.818210365.58  245.2110385.75239.1938
10405.92244.617810426.09  246.2810446.26246.563110466.43243.405610496.86247.1947
10588.02251.434310667.78251.192510713.36249.290710747.54241.272610758.93245.8109
10781.72248.593110837.08248.945410878.81243.705210962.25  251.9111010.78 253.828
#Mann= 3 , 0 , 0
9281.871    0.04       09281.871    0.04       011010.78    0.04       0
#XS Ineff= 2 , 0
       0                               0
Bank Sta=9281.871,11010.78
Exp/Cntr=0.3,0.1

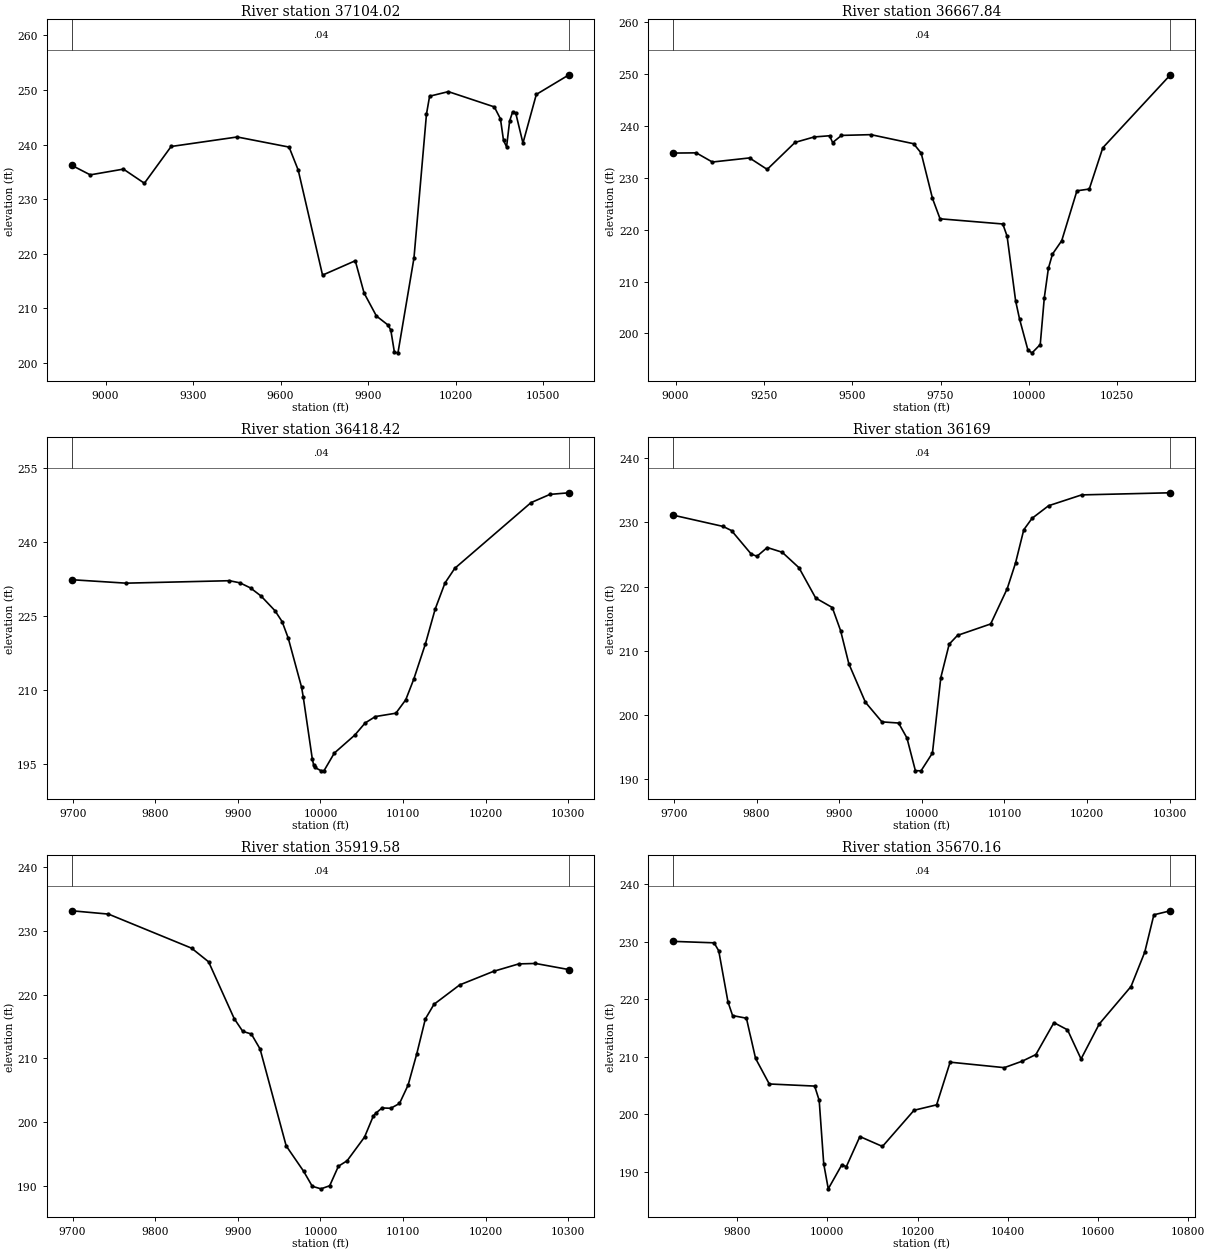
Type RM Length L Ch R = 1 ,37104.02,436.183600,436.183600,436.183600
XS GIS Cut Line= 6
715209.593819342726614.111640033714962.025593162726392.986329064
714620.358926475726242.986329064714303.692259848726205.486329064
714078.692259878726317.986329079713701.368341744726148.036015928
#Sta/Elev= 30
8884.341236.18188947.438234.44399061.141235.49659133.039232.9078  9224.7239.6365
9451.244 241.3799629.121239.52889660.403235.31179743.821216.08699856.005218.7191
9886.238212.80559928.512208.59989968.198206.95589977.853206.01889990.188201.9497
10002.36201.861210057.18219.1995 10100.1245.573210110.83248.843510175.13249.6798
10332.68246.884610353.69244.6897 10364.2240.7461 10374.7239.5776 10385.2244.3112
10395.71246.011310406.21245.732910430.85  240.2610476.66249.166910588.82 252.766
#Mann= 3 , 0 , 0
8884.341    0.04       08884.341    0.04       010588.82    0.04       0
#XS Ineff= 2 , 0
       0                               0
Bank Sta=8884.341,10588.82
Exp/Cntr=0.3,0.1

Type RM Length L Ch R = 1 ,36667.84,249.419100,249.419100,249.419100
XS GIS Cut Line= 6
715257.774247184726573.425945412715069.243740171726362.507621512
714938.506221145726244.034168705714840.912983149726181.468358129
714558.710811913726047.651872858714279.516627789725613.054802224
#Sta/Elev= 30
8993.581 234.8029058.605234.84459104.209233.07449209.477 233.8659259.419231.6526
9338.295236.86039392.398237.91119435.999238.14459444.594236.82869469.705238.2111
9552.945238.35679673.793 236.6059695.165234.80269727.223 226.0499748.595222.1228
9926.155221.11989938.329218.77059962.501206.27419973.521202.79969997.494  196.74
10009.05196.258810032.13197.862810043.67206.911410055.21212.563510066.75215.3083
10092.95217.901810135.99227.5239 10170.9227.861110209.22235.827710400.63249.9086
#Mann= 3 , 0 , 0
8993.581    0.04       08993.581    0.04       010400.63    0.04       0
#XS Ineff= 2 , 0
       0                               0
Bank Sta=8993.581,10400.63
Exp/Cntr=0.3,0.1

Type RM Length L Ch R = 1 ,36418.42,249.419100,249.419100,249.419100
XS GIS Cut Line= 6
714883.268690649726057.921059634714796.917660275725940.072045119
714706.900256287725826.305974244714645.753908076725743.678832629
714597.939034258725668.872895266714539.844845905725564.778078636
#Sta/Elev= 30
9699.009232.37969764.616231.68179889.831232.17919902.583231.74339915.335230.7088
9928.087229.06829944.895 226.099 9953.59 223.8769961.011220.51719977.127210.5683
9979.094208.6616 9990.18195.93849991.824194.73849993.308194.2632   10001193.5813
10004.37193.624610016.79197.185810041.64200.850110054.06203.291610066.48204.5995
10091.33205.282410103.27208.008910112.94 212.17310127.01219.318210138.88 226.408
10150.75231.707410162.61234.6896 10254.9248.025710277.81249.700510300.96250.0297
#Mann= 3 , 0 , 0
9699.009    0.04       09699.009    0.04       010300.96    0.04       0
#XS Ineff= 2 , 0
       0                               0
Bank Sta=9699.009,10300.96
Exp/Cntr=0.3,0.1

Type RM Length L Ch R = 1 ,   36169,249.419200,249.419200,249.419200
XS GIS Cut Line= 6
714939.255078077725992.946015888 714910.61142231 725882.89128421
714897.780037303725784.479848577714899.321055378725738.200138104
 714919.59972755725590.674848807714911.621567645725397.731804691
#Sta/Elev= 30
9699.096231.12839759.369229.37699769.635228.72549793.461225.07139800.433224.7245
9812.864226.09229830.993225.35219851.259222.94729871.526218.21939891.596216.7469
 9901.63213.15789911.664207.97479931.676201.99879951.687 198.937 9971.84198.7575
9981.953196.43239992.164191.3419    9999191.311910012.82194.083310022.96205.8409
 10033.1211.042310043.17212.4068 10083.3 214.18610103.36219.689810113.38223.6713
10123.38228.856710133.38230.634210153.38232.596610193.38234.285710300.92234.6156
#Mann= 3 , 0 , 0
9699.096    0.04       09699.096    0.04       010300.92    0.04       0
#XS Ineff= 2 , 0
       0                               0
Bank Sta=9699.096,10300.92
Exp/Cntr=0.3,0.1

Type RM Length L Ch R = 1 ,35919.58,249.419100,249.419100,249.419100
XS GIS Cut Line= 6
715093.418518378726069.212764855715090.180998008725994.689579953
715098.906879476725923.867432376715115.789549801725859.032398974
715191.199016719725628.324128039715217.727495487725484.798961225
#Sta/Elev= 30
 9699.07233.16399743.416232.64259843.991227.29579864.636  225.159895.636216.2292
9905.969 214.2359916.385213.8126 9926.92211.47099958.528196.2557  9979.6192.2788
9990.136189.908410000.65189.507910011.21189.992710021.77193.055810032.33193.9206
10053.45197.646710064.01200.940410067.24201.405410074.58202.209310085.14202.1564
 10095.7202.907310106.15205.800710116.59210.691110127.03216.188710137.47218.4801
10168.54221.521210209.56223.656710240.11224.823410260.32224.892310300.95223.9276
#Mann= 3 , 0 , 0
 9699.07    0.04       0 9699.07    0.04       010300.95    0.04       0
#XS Ineff= 2 , 0
       0                               0
Bank Sta=9699.07,10300.95
Exp/Cntr=0.3,0.1

Type RM Length L Ch R = 1 ,35670.16,470.564600,470.564600,470.564600
XS GIS Cut Line= 6
715435.713709693726201.709681961715394.524798363726045.340508372
715371.617232263725858.141855359715365.878344595725389.943794131
715347.366389453725191.344292164715332.407102108725108.959607154
#Sta/Elev= 30
 9658.51230.0635    9749229.81069759.345228.42419779.813219.54539790.036217.1753
9820.701216.71899840.963209.73519871.356 205.2979971.947204.93059982.002202.4499
9992.057191.428510002.12187.084610032.18191.259510042.19190.941810072.22196.1634
10122.26194.447210192.26200.730910242.26201.671210272.26209.083710392.27208.1317
10432.28 209.26310462.29210.405610502.34215.9456 10532.4214.700410562.46  209.64
10602.71215.7068 10673.2222.2229 10703.6 228.18110723.89234.678710760.62235.3769
#Mann= 3 , 0 , 0
 9658.51    0.04       0 9658.51    0.04       010760.62    0.04       0
#XS Ineff= 2 , 0
       0                10385.72       0
Bank Sta=9658.51,10760.62
Exp/Cntr=0.3,0.1