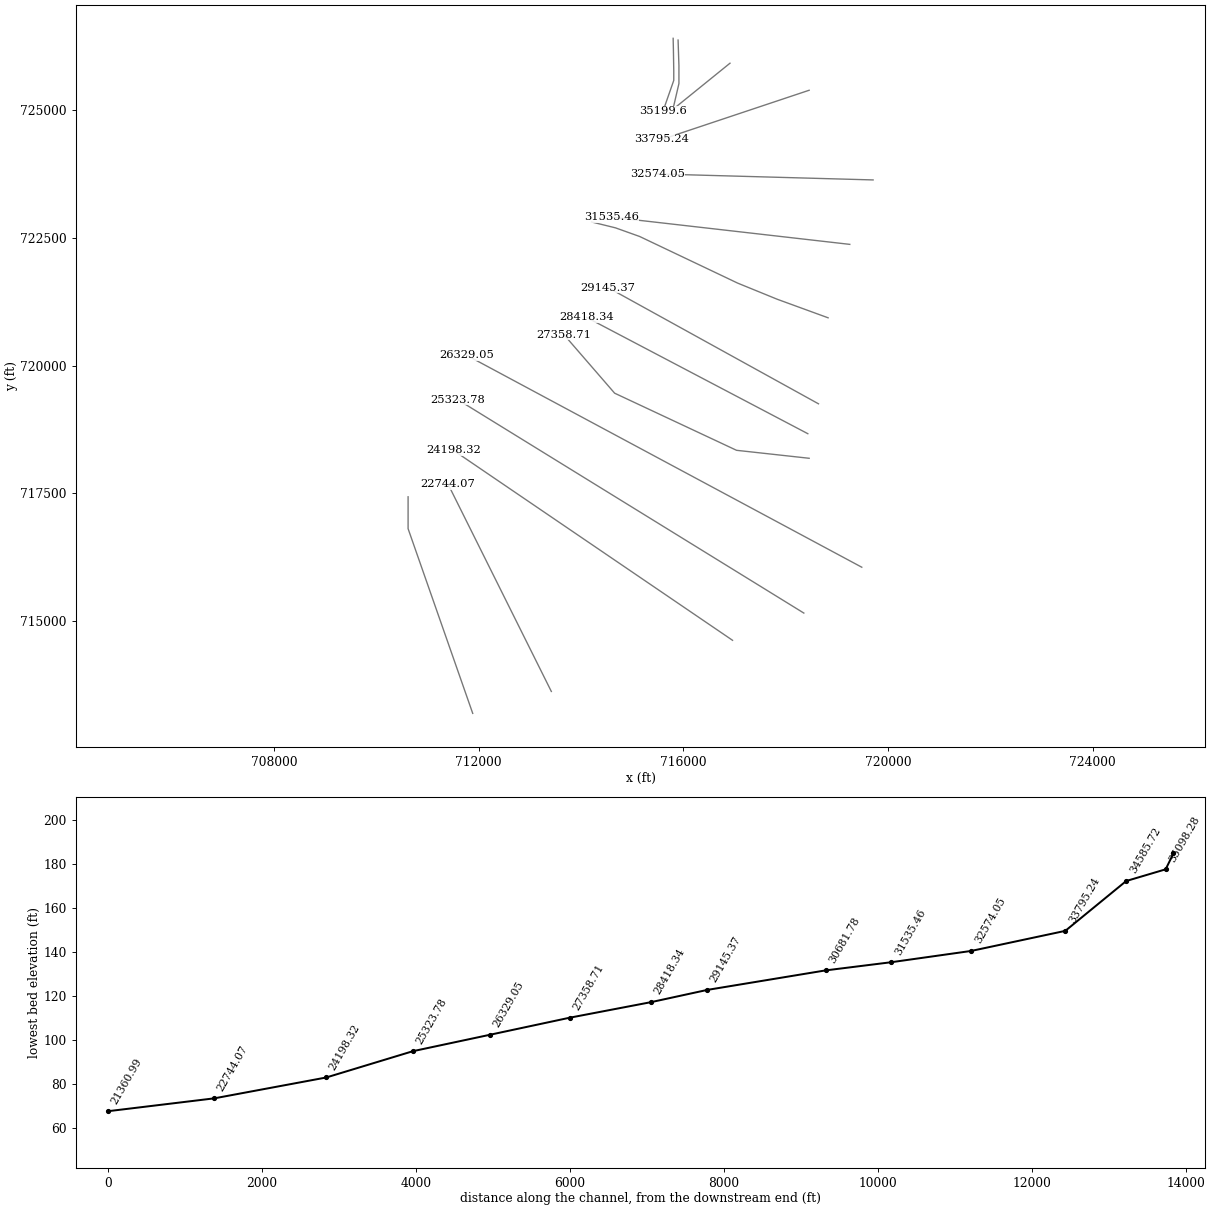
HEC-RAS study 4932_ras.prj: 4932

--- 4932_ras.g01 (geometry) --- (continued)

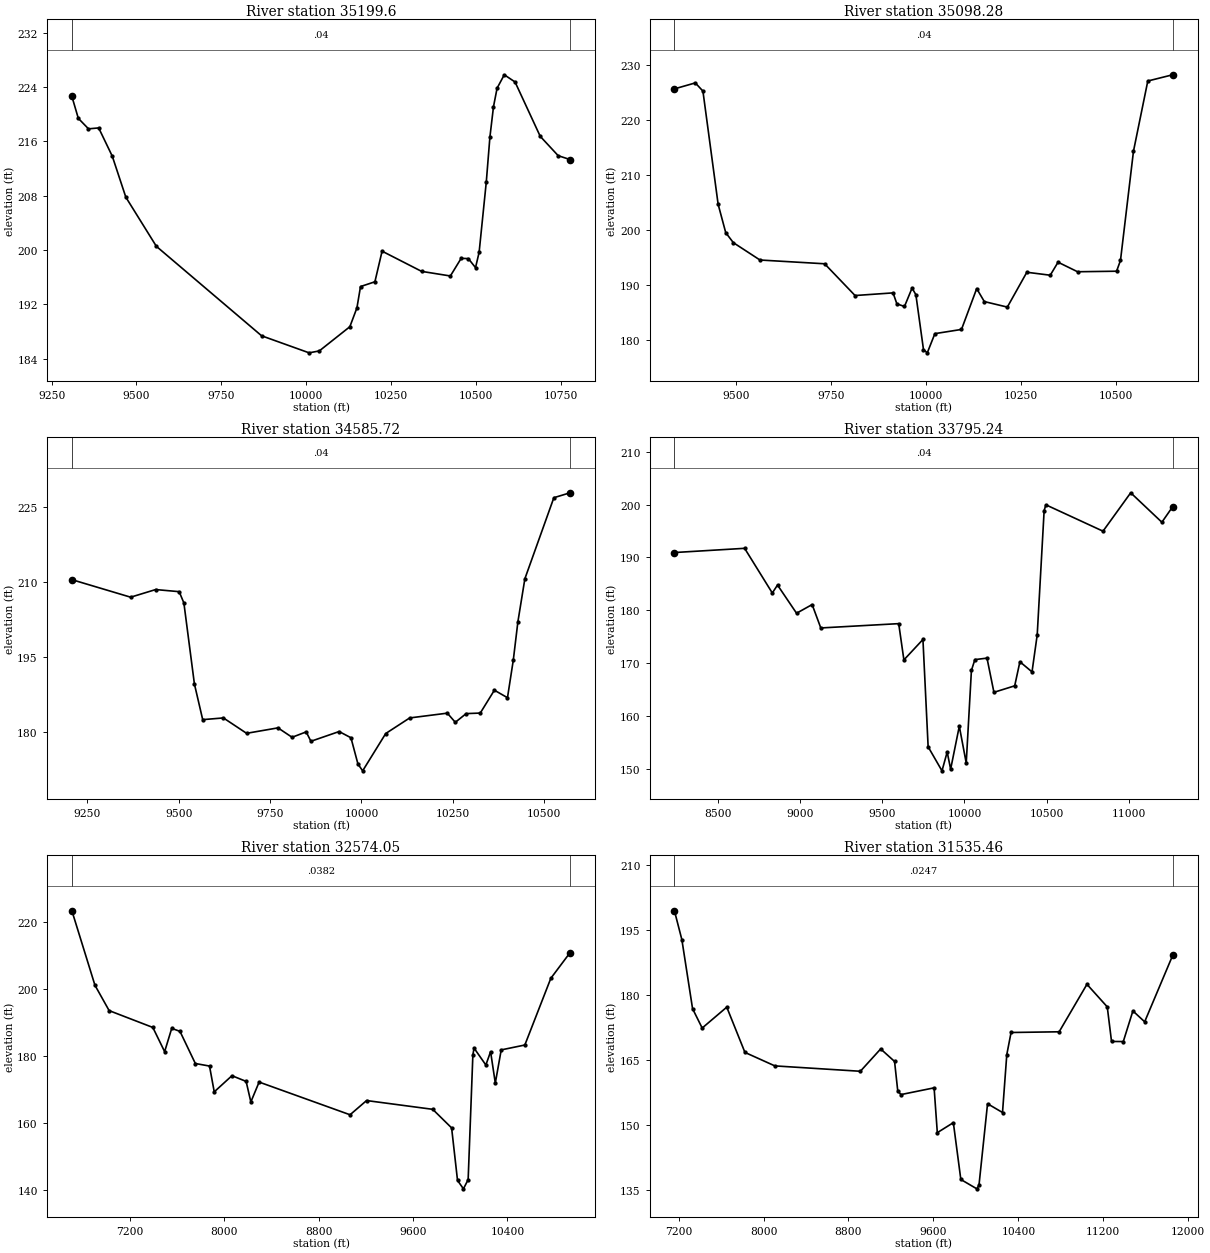
Type RM Length L Ch R = 1 , 35199.6,101.311100,101.311100,101.311100
XS GIS Cut Line= 5
715802.237932885726413.922493599715807.099044049726193.783604718
 715814.12100851725780.443691022 715814.12100851725589.471468783
715602.315452928724981.832579888
#Sta/Elev= 30
9309.628222.60829328.555219.38089358.563217.8371 9388.57217.9715 9428.58213.8205
9468.589207.77569558.608200.54489868.653187.381610008.66184.873710038.66185.1562
10128.66188.716910149.52191.490410160.11194.627610202.47195.329510223.65199.8345
10340.14196.861710424.86196.184210456.63 198.77710477.81198.743510498.99197.4117
10509.58199.667710530.76210.051410541.35216.624110551.94221.103110562.53223.8215
10583.71225.792610615.48224.730410689.61216.736310742.56213.886910777.69213.3155
#Mann= 3 , 0 , 0
9309.628    0.04       09309.628    0.04       010777.69    0.04       0
#XS Ineff= 2 , 0
       0                10060.62       0
Bank Sta=9309.628,10777.69
Exp/Cntr=0.3,0.1

Type RM Length L Ch R = 1 ,35098.28,512.560200,512.560200,512.560200
XS GIS Cut Line= 4
715898.561828901726379.913412389715915.054884453725879.045356851
715915.054884453725527.482856837715811.756273349725081.302301299
#Sta/Elev= 30
9337.884225.64879392.827226.73429412.838225.24569452.859204.6547 9472.87199.4918
9492.881197.67359562.919194.51799733.011193.83279813.055 188.0579913.069188.5384
9923.069186.54339943.069186.06329963.069189.41999973.069 188.2099993.069 178.229
10003.07177.632310023.07 181.12510093.07 181.88910133.07189.316510153.07186.9586
10213.66185.953710264.99 192.29110326.57191.7513 10347.1194.119110398.42192.3831
10501.07192.480310511.33194.439510545.52214.313410583.19227.079610648.57228.2127
#Mann= 3 , 0 , 0
9337.884    0.04       09337.884    0.04       010648.57    0.04       0
#XS Ineff= 2 , 0
       0                10116.26       0
Bank Sta=9337.884,10648.57
Exp/Cntr=0.3,0.1

Type RM Length L Ch R = 1 ,34585.72,790.483100,790.483100,790.483100
XS GIS Cut Line= 2
716913.051802069725926.339300454715854.024024278725066.964300454
#Sta/Elev= 30
9207.398210.54849368.226207.04229436.698208.57019501.089208.14789513.967205.8919
9542.797189.6793 9565.48 182.5469622.148182.88839685.629179.81059771.532180.9005
9810.167179.01639848.802 180.097 9861.68178.2156 9938.95180.16629971.292178.9239
9990.463173.668910003.34172.304410066.51179.770810132.12182.888310235.15183.8441
10256.95182.011710286.66183.7535 10325.3183.861910363.93188.437110399.79 186.937
10415.66 194.42110428.32202.1356 10447.4210.732310526.75226.946510571.24227.9314
#Mann= 3 , 0 , 0
9207.398    0.04       09207.398    0.04       010571.24    0.04       0
#XS Ineff= 2 , 0
       09349.532        10183.64       0
Bank Sta=9207.398,10571.24
Exp/Cntr=0.3,0.1

Type RM Length L Ch R = 1 ,33795.24,1221.196300,1221.196300,1221.196300
XS GIS Cut Line= 2
 718460.36082986725396.391383797715582.756663203724432.849717125
#Sta/Elev= 30
8233.685190.93438661.166191.73158829.897183.27648861.535184.78298977.537 179.446
9072.449181.08919125.177176.66199599.734177.47849631.371170.61419747.374174.4802
9779.011 154.1699863.377149.62349895.014153.18269916.105149.94089968.834158.0678
10011.02151.106110042.65168.624310063.74170.671910137.56 170.95310179.75164.4818
 10306.3165.710310337.93170.264910411.75168.348410443.39175.360910485.57198.8746
10496.12199.963810844.13194.975711012.86 202.24211202.68196.667411268.32199.6023
#Mann= 3 , 0 , 0
8233.685    0.04       08233.685    0.04       011268.32    0.04       0
#XS Ineff= 2 , 0
       09813.617                       0
Bank Sta=8233.685,11268.32
Exp/Cntr=0.3,0.1

Type RM Length L Ch R = 1 ,32574.05,1038.586700,1038.586700,1038.586700
XS GIS Cut Line= 2
 719710.36082986723638.578883797 715491.61082986723755.766383797
#Sta/Elev= 30
6710.366223.24366905.802201.06737025.848193.53287395.991188.5217 7496.03181.3165
7556.053188.2539 7626.08187.3492 7756.13177.78817876.176177.03147916.192169.3536
 8066.25174.16128186.296172.46518226.311166.35368296.338 172.2649066.635162.5333
9206.689 166.7679766.905164.15499926.967158.62689976.986143.004810027.01140.4901
10067.02143.235110107.04180.349810117.04182.377510217.08177.342110257.09 181.312
10297.11171.965210347.13181.840310547.21183.292910767.29203.142310930.74210.8043
#Mann= 3 , 0 , 0
6710.366  0.0382       06710.366  0.0382       010930.74  0.0382       0
#XS Ineff= 2 , 0
       09357.075                       0
Bank Sta=6710.366,10930.74
Exp/Cntr=0.3,0.1

Type RM Length L Ch R = 1 ,31535.46,853.680400,853.680400,853.680400
XS GIS Cut Line= 2
719254.631663173722375.558050454 714593.17332986722909.412217125
#Sta/Elev= 30
7160.933199.4064 7231.02192.75257331.674176.85967422.262172.39237653.765177.2071
7824.877166.78068106.707163.67538911.936162.43599103.178167.58369234.028164.6986
9264.224 157.876 9294.42157.06759606.447158.62029636.643148.29549787.623150.6005
9858.081137.512510009.06135.354210029.19136.234910109.71154.958310250.63152.9372
10290.89166.269810331.15171.368810784.09171.531511045.79182.469411237.04177.2721
 11277.3169.302411388.02169.2815 11478.6176.338711589.32173.829711852.86189.1138
#Mann= 3 , 0 , 0
7160.933  0.0247       07160.933  0.0247       011852.86  0.0247       0
#XS Ineff= 2 , 0
       09557.849                       0
Bank Sta=7160.933,11852.86
Exp/Cntr=0.3,0.1

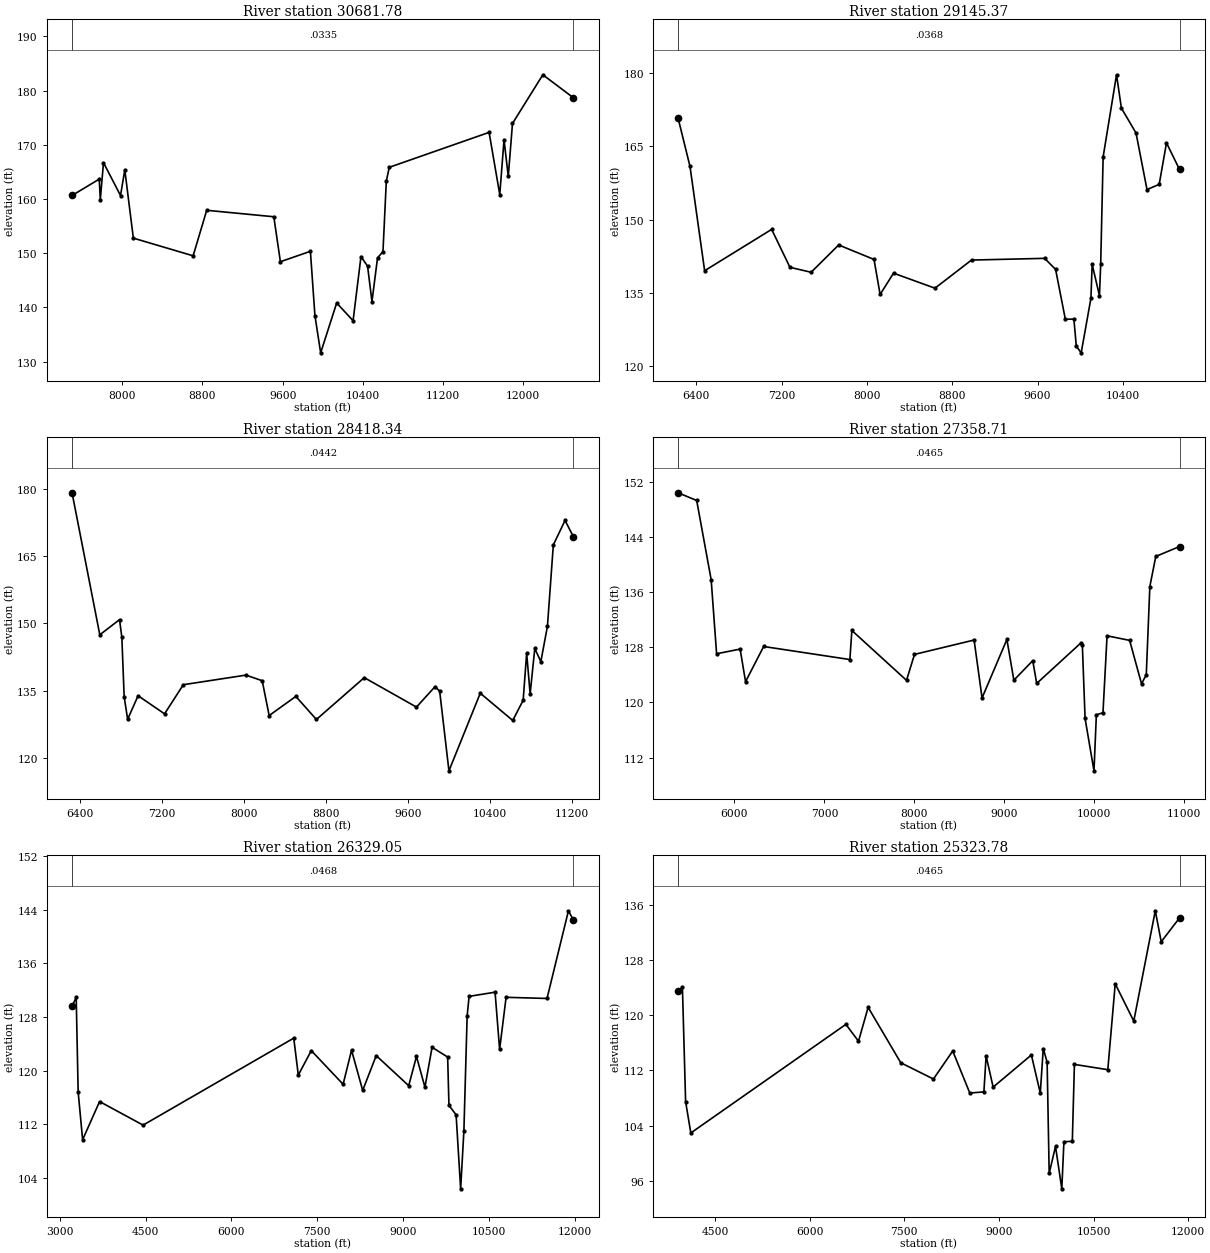
Type RM Length L Ch R = 1 ,30681.78,1536.408800,1536.408800,1536.408800
XS GIS Cut Line= 6
718830.674589679720936.234379883717837.749622742721299.399360111
717064.548512613721615.509158873  715147.3661116722530.060756579
714675.209196873722699.318582127714207.140606892722815.048782723
#Sta/Elev= 30
7499.053160.6499  7770.3163.6625 7780.91159.88577812.737166.69587982.561160.6383
8025.202165.36988110.484 152.7818706.899149.51938842.275157.91569511.687156.7237
9577.388148.43029876.752  150.359921.817 138.5069979.047131.625310138.88140.8214
10302.46137.551810381.21149.379610446.99147.611310490.85141.085310546.33149.1396
10600.68150.288310633.97163.314110663.75165.844711659.23172.2851 11765.7160.8272
11808.25170.905711850.62 164.15911892.66173.931312195.36 182.90912500.96178.6619
#Mann= 3 , 0 , 0
7499.053  0.0335       07499.053  0.0335       012500.96  0.0335       0
#XS Ineff= 2 , 0
       08933.387                       0
Bank Sta=7499.053,12500.96
Exp/Cntr=0.3,0.1

Type RM Length L Ch R = 1 ,29145.37,727.032900,727.032900,727.032900
XS GIS Cut Line= 2
718642.652496547719250.558050469714528.069163173721529.203883812
#Sta/Elev= 30
6228.243170.71786339.871160.84466477.043139.53397105.752147.98517277.218140.2331
7475.886139.2188 7734.46144.79958065.961141.83958123.116134.67798248.858139.0351
8637.514135.96428980.446141.71359666.309142.06529769.189139.80229860.637129.6078
9940.655129.65329963.517124.102610009.24122.746510100.69133.926910112.12140.8484
10180.71 134.42110192.14140.8391   10215162.788310340.74179.5946 10386.3172.7794
10523.64167.686910626.52156.132810740.83157.183510809.42165.671210931.65160.2296
#Mann= 3 , 0 , 0
6228.243  0.0368       06228.243  0.0368       010931.65  0.0368       0
#XS Ineff= 2 , 0
       0 7918.19                       0
Bank Sta=6228.243,10931.65
Exp/Cntr=0.3,0.1

Type RM Length L Ch R = 1 ,28418.34,1059.622300,1059.622300,1059.622300
XS GIS Cut Line= 2
718434.319163203718664.620550454714111.402496517720943.266383812
#Sta/Elev= 30
6324.911179.04916595.441147.45646787.612150.83166810.221 146.9116832.829133.6633
6866.741128.65966968.479133.90827226.441129.87777409.342136.35758019.767 138.493
8178.025137.24338245.851129.49818505.847133.7563 8706.19128.62159172.793137.9314
9681.481131.37789862.347 135.9239907.564134.92839997.997117.199110303.21134.4652
10619.73128.407510721.46132.902310755.38143.371210789.29134.309510834.51144.4158
10893.64141.491110957.98 149.37611015.37167.455911129.55172.896811211.61169.2488
#Mann= 3 , 0 , 0
6324.911  0.0442       06324.911  0.0442       011211.61  0.0442       0
#XS Ineff= 2 , 0
       07996.225                       0
Bank Sta=6324.911,11211.61
Exp/Cntr=0.3,0.1

Type RM Length L Ch R = 1 ,27358.71,1029.668900,1029.668900,1029.668900
XS GIS Cut Line= 4
 718460.36082986718182.849717125717041.089996487718339.099717125
714658.277496517719458.891383797713668.694163173 720604.72471714
#Sta/Elev= 30
5373.663 150.3845580.265149.26645741.231137.78765801.594127.05616063.165127.7373
6123.527123.01136324.736128.11117283.353126.21917305.452  130.437913.158123.2067
8001.552126.96528664.504129.04778752.897120.65779029.127129.12819106.472123.2261
9316.407126.05539360.603122.75999852.425128.63199867.724128.38489898.323117.6842
9997.349110.094610023.78118.208510097.22118.512710142.69129.659810393.74128.9975
10525.87122.702510578.73124.022510618.37136.803710684.43 141.16110948.33142.5942
#Mann= 3 , 0 , 0
5373.663  0.0465       05373.663  0.0465       010948.33  0.0465       0
#XS Ineff= 2 , 0
       07466.215                       0
Bank Sta=5373.663,10948.33
Exp/Cntr=0.3,0.1

Type RM Length L Ch R = 1 ,26329.05,1005.260400,1005.260400,1005.260400
XS GIS Cut Line= 2
719489.006663173716047.433050469711767.652496487720201.078883797
#Sta/Elev= 30
 3212.98129.6091 3285.66130.90193319.726116.8172 3397.82109.69093694.444115.3833
4455.235111.87017089.618124.83467169.104119.32637396.206122.97597952.605117.9559
8100.222123.03398294.964 117.0448531.715122.2298 9099.47117.74559235.731122.1037
9383.348117.51529508.254123.46919780.776 122.0169803.486114.81619928.392113.4071
10007.88102.373910064.65 111.02510121.43128.105810155.49131.0601 10609.7131.6828
10689.18123.151110802.73130.919711518.11130.746511892.82 143.81611980.65142.4091
#Mann= 3 , 0 , 0
 3212.98  0.0468       0 3212.98  0.0468       011980.65  0.0468       0
#XS Ineff= 2 , 0
       07029.735        10326.86       0
Bank Sta=3212.98,11980.65
Exp/Cntr=0.3,0.1

Type RM Length L Ch R = 1 ,25323.78,1125.463300,1125.463300,1125.463300
XS GIS Cut Line= 2
718356.194163203715148.995550469711598.381663203719328.683050469
#Sta/Elev= 30
3916.023123.5039 3984.47124.01534035.008107.48554117.315102.94656574.767118.6616
6774.655116.21916927.511121.11887444.441113.10597962.227110.75188267.939114.8075
8538.376108.72588761.781108.89098797.055114.09778908.274109.58029514.302  114.23
  9655.4108.71229702.432115.15699763.761113.19229796.497 97.10529896.837101.0063
9996.38694.8646210029.91101.670210162.99101.744110196.27112.867810725.39112.1014
10842.97124.523211136.93119.132911477.91135.093211571.98130.606911861.95134.0631
#Mann= 3 , 0 , 0
3916.023  0.0465       03916.023  0.0465       011861.95  0.0465       0
#XS Ineff= 2 , 0
       07168.346                       0
Bank Sta=3916.023,11861.95
Exp/Cntr=0.3,0.1

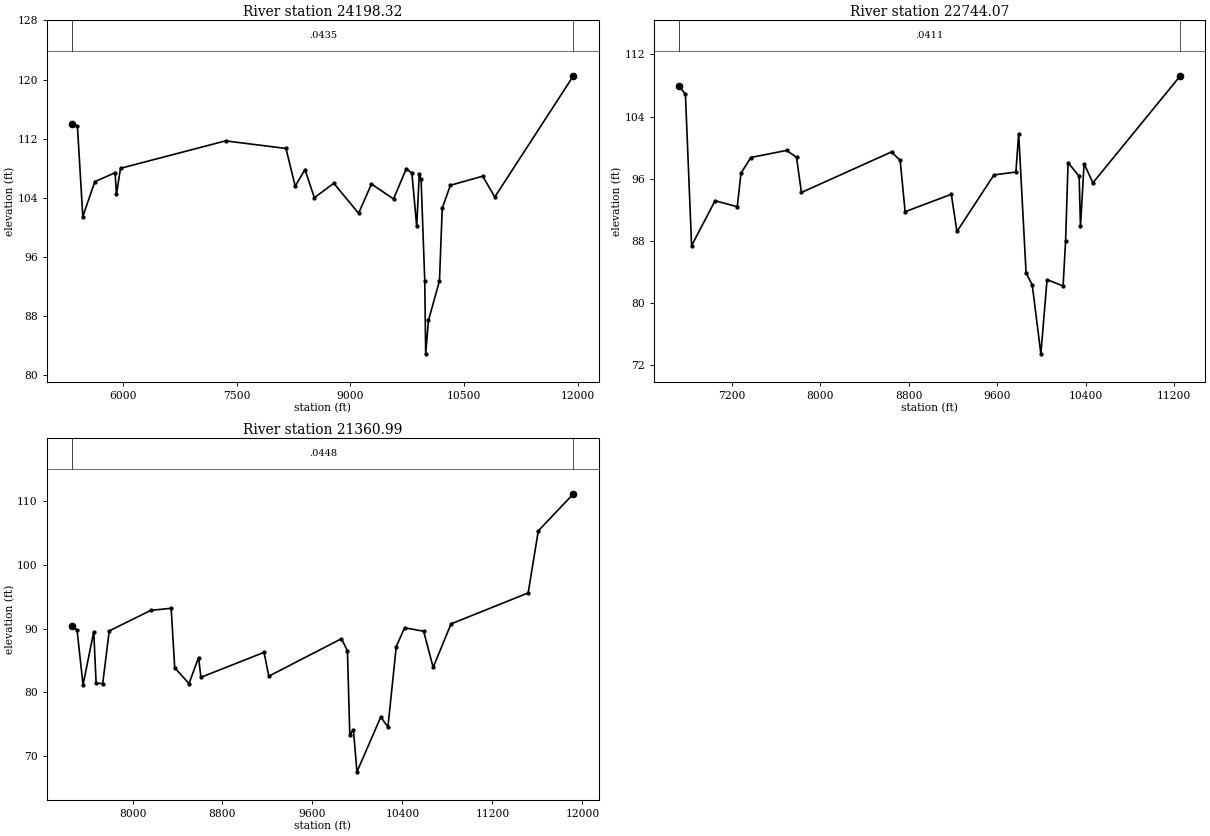
Type RM Length L Ch R = 1 ,24198.32,1454.254100,1454.254100,1454.254100
XS GIS Cut Line= 2
716962.964996487714615.141383797 711507.23582983718339.099717125
#Sta/Elev= 30
 5332.59113.93725403.291113.72415474.242101.46415632.813106.19435899.952107.3936
 5917.69104.46775970.903107.99227354.459111.7031 8151.17110.67758272.245 105.578
8400.994107.82538525.159104.0152 8780.76105.97089107.662101.90639277.166105.8745
9567.746103.84299737.251107.96389809.896107.31379873.239100.14849906.756107.1983
9930.971106.48299979.40192.744369991.50882.8961210027.8387.4119110173.1292.76283
10209.44102.585210316.69105.699210742.17106.923710902.04104.114311938.11120.5103
#Mann= 3 , 0 , 0
 5332.59  0.0435       0 5332.59  0.0435       011938.11  0.0435       0
#XS Ineff= 2 , 0
       0 7947.37                       0
Bank Sta=5332.59,11938.11
Exp/Cntr=0.3,0.1

Type RM Length L Ch R = 1 ,22744.07,1383.076800,1383.076800,1383.076800
XS GIS Cut Line= 2
 713421.29832986713612.537217125711403.069163173717675.037217125
#Sta/Elev= 30
6720.221107.98536778.801 106.8446834.63187.341717046.78693.144077247.77592.36778
7281.27396.688077370.601 98.71697694.41799.635647783.745 98.74127828.40994.20763
 8643.5399.437918721.69398.340188766.35791.730429184.279 93.97039235.33189.17659
9570.31296.471869768.65996.842139793.633101.79259860.62983.850219916.45982.27617
9994.62273.3995310050.4582.9727910195.61 82.139910218.1887.9528310240.6698.05112
10340.7796.3012910353.0489.8355510385.4397.9122710465.4295.4542811256.43109.2549
#Mann= 3 , 0 , 0
6720.221  0.0411       06720.221  0.0411       011256.43  0.0411       0
#XS Ineff= 2 , 0
       08387.605                       0
Bank Sta=6720.221,11256.43
Exp/Cntr=0.3,0.1

Type RM Length L Ch R = 1 ,21360.99,1620.040400,1620.040400,1620.040400
XS GIS Cut Line= 3
711884.839996517713182.849717125710621.819163203716802.641383812
710621.819163203717427.641383812
#Sta/Elev= 30
7462.10190.408557506.74389.795487559.699 81.1728 7655.0289.532937676.20381.44375
7734.80481.391717792.70789.66451  8163.4 92.89258343.45293.213728375.22583.87273
 8502.3281.38751 8587.0585.485278608.23382.381869169.56986.293289211.93482.55822
    985888.435069910.95786.542739932.13973.290969963.91374.178049995.68767.53381
10207.5176.1456410271.0674.56149 10345.287.1938110419.3490.15294 10588.889.61419
10673.5383.93142 10832.490.7640111518.2795.6264411608.27105.367911920.91111.1945
#Mann= 3 , 0 , 0
7462.101  0.0448       07462.101  0.0448       011920.91  0.0448       0
#XS Ineff= 2 , 0
       08318.712                       0
Bank Sta=7462.101,11920.91
Exp/Cntr=0.3,0.1