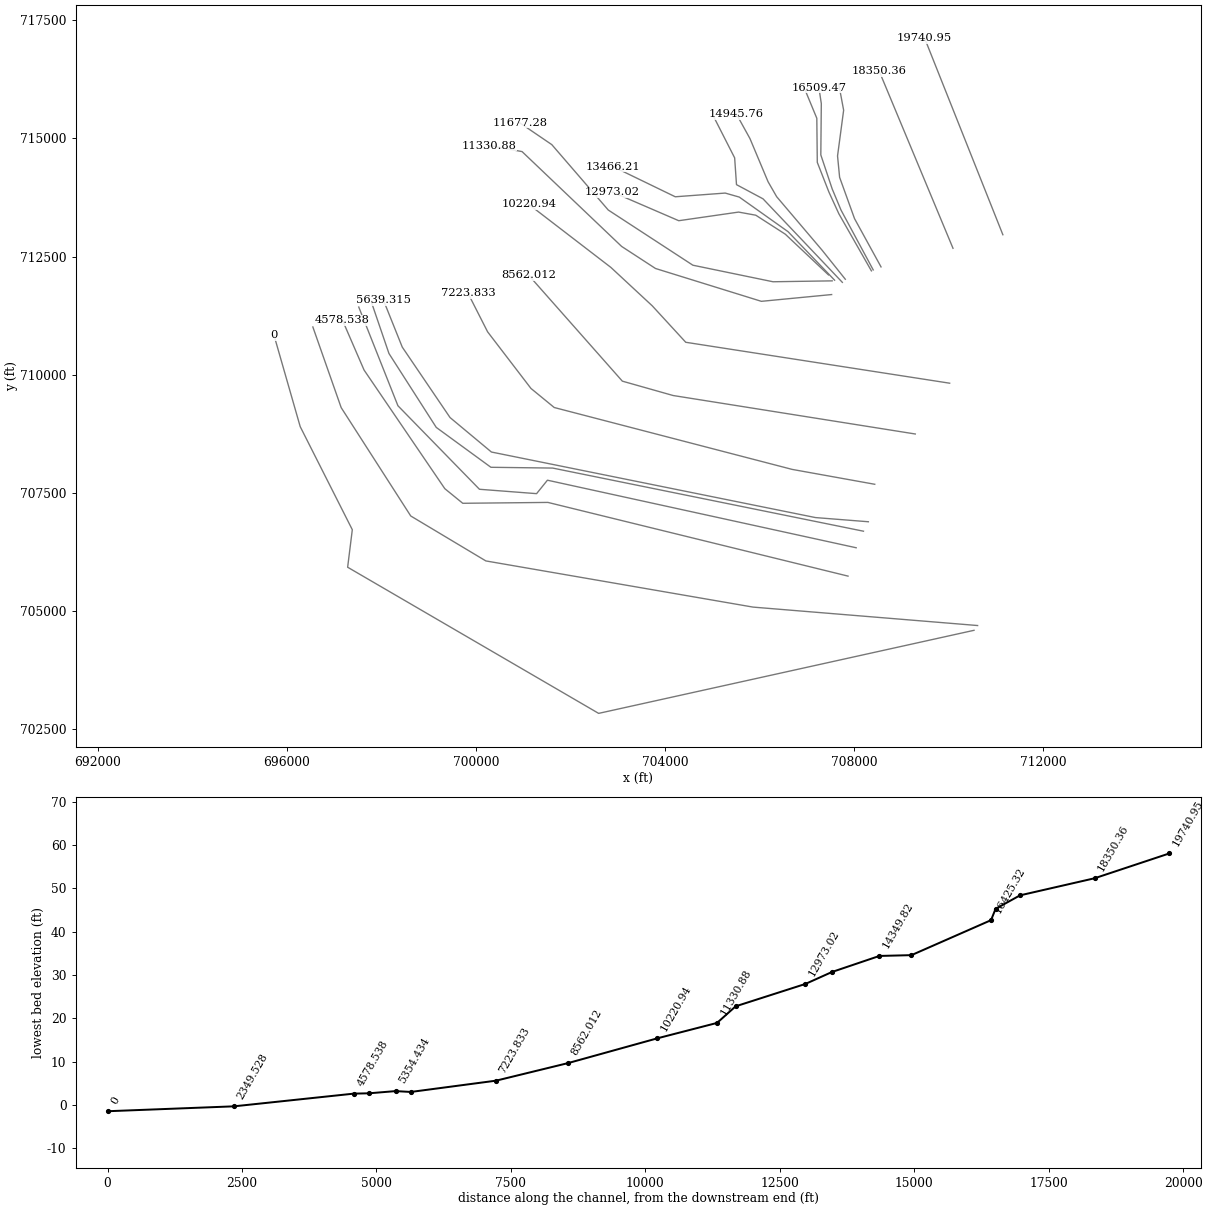
HEC-RAS study 4932_ras.prj: 4932

--- 4932_ras.g01 (geometry) --- (continued)

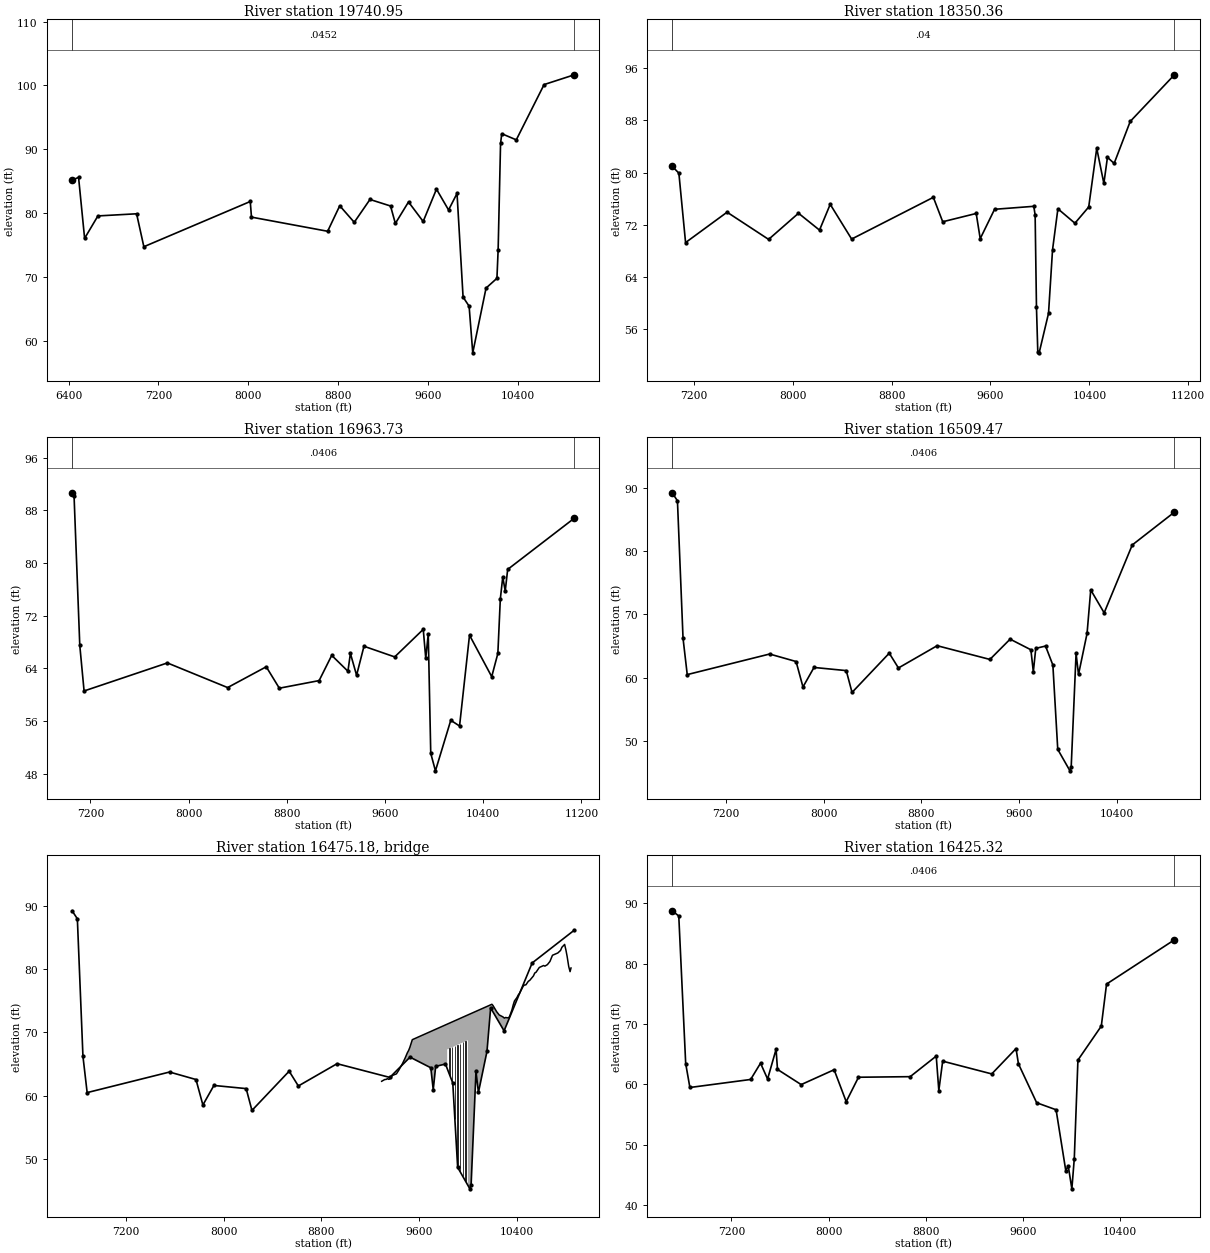
Type RM Length L Ch R = 1 ,19740.95,1390.592100,1390.592100,1390.592100
XS GIS Cut Line= 2
711142.652496487712961.495550454709489.006663173717115.141383812
#Sta/Elev= 30
6431.66585.129576489.25485.603886543.07176.034536661.46879.549387005.89579.88532
7070.47574.721018017.65181.811448028.414 79.36068706.50677.144128814.13981.14246
  8943.378.548659083.22382.12816  9266.281.106819309.25478.371229426.26281.74028
9556.81178.678649675.20883.747659782.84280.483939858.18583.074129912.00266.83011
9965.81965.398259998.10958.0875110116.5168.2399910213.3869.7692110224.1474.24636
10245.6790.9083710256.4392.4377710385.5991.4735210633.15 100.13910902.38101.6751
#Mann= 3 , 0 , 0
6431.665  0.0452       06431.665  0.0452       010902.38  0.0452       0
#XS Ineff= 2 , 0
       06809.387                       0
Bank Sta=6431.665,10902.38
Exp/Cntr=0.3,0.1

Type RM Length L Ch R = 1 ,18350.36,1386.631400,1386.631400,1386.631400
XS GIS Cut Line= 2
710087.964996517712675.037217125708525.464996517 716425.03721714
#Sta/Elev= 30
7025.81480.944827079.94179.903477134.10769.255647469.94173.916477805.77469.74497
8047.52373.755878217.44171.169088304.10775.119748477.44169.795249138.27476.19436
9214.10772.448299484.94173.719729517.44169.856339633.52374.360359950.77474.81668
9961.60773.494429972.44159.333219983.27452.414349994.10752.3507810069.9458.41065
10102.4468.1572210145.7774.4351310283.5272.2258210394.94 74.712510459.9483.70999
10517.5278.3306410546.6182.3265110600.7781.3942410730.77   87.8311088.3194.98463
#Mann= 3 , 0 , 0
7025.814    0.04       07025.814    0.04       011088.31    0.04       0
#XS Ineff= 2 , 0
       0                               0
Bank Sta=7025.814,11088.31
Exp/Cntr=0.3,0.1

Type RM Length L Ch R = 1 ,16963.73,454.257000,454.257000,454.257000
XS GIS Cut Line= 6
708566.010883629712281.177732393708005.793550432713301.702858135
707690.056439877 714175.94608584707646.268267483714627.484906197
707775.293613911715595.409583151707671.770059099716147.013673683
#Sta/Elev= 30
7050.30490.678547066.40890.167397113.01467.463077147.96860.54648 7826.6564.81112
8317.60561.064078632.33664.22496 8738.9160.968259063.27562.124569165.83665.95852
 9297.9163.547339318.07566.255169368.43862.937519428.62467.345689678.969 65.7258
9911.68769.914229932.05265.522679952.41769.185459972.78351.0695610010.9748.40527
10135.9956.0902310207.4755.2203710288.6469.0273410469.5962.72158 10519.666.25739
 10539.674.51731 10559.677.87298 10579.6 75.739710599.6379.0257311142.7786.81558
#Mann= 3 , 0 , 0
7050.304  0.0406       07050.304  0.0406       011142.77  0.0406       0
#XS Ineff= 2 , 0
       07300.967                       0
Bank Sta=7050.304,11142.77
Exp/Cntr=0.3,0.1

Type RM Length L Ch R = 1 ,16509.47,84.152400,84.152400,84.152400
XS GIS Cut Line= 6
708400.803251624712217.384756774707720.054399669713482.297793671
707532.682483613713931.376033977707292.581148744 714650.27799575
 707302.99781543715735.694662407707251.326609164716074.260766461
#Sta/Elev= 30
6758.98889.203136802.07587.939696847.89466.221436882.25860.491617556.91363.74101
7773.42962.556167829.98458.534997920.21861.620378184.30461.123088231.65657.67689
8536.324 63.87268611.558 61.53788928.59665.055559360.583 62.88689526.07566.09018
9696.07664.412719716.07660.946339736.07664.631999816.07665.000349876.07762.00154
9916.07748.6823510016.0845.2945710026.08 45.864110066.0863.8259510086.0860.51682
10156.0866.9969810186.0973.8635110296.1170.2429310526.1680.96331 10871.486.14659
#Mann= 3 , 0 , 0
6758.988  0.0406       06758.988  0.0406       0 10871.4  0.0406       0
#XS Ineff= 2 , 0
       07091.783                       0
Bank Sta=6758.988,10871.4
Exp/Cntr=0.3,0.1

Type RM Length L Ch R = 3 ,16475.18,,,
BEGIN DESCRIPTION:
END DESCRIPTION:
Bridge Culvert--1,0,-1,-1, 0
Deck Dist Width WeirC Skew NumUp NumDn MinLoCord MaxHiCord MaxSubmerge Is_Ogee
24.316200,35.520000,2.6,0, 58, 58, , , 0.95, 0, 0,0,,
 9293.76 9319.38 9330.00 9340.61 9352.53 9361.85 9383.08 9414.58 9434.59 9464.60
 9484.60 9504.61 9514.61 9524.61 9544.62 9830.00 9830.0010000.0010000.0010196.33
10204.8010235.6810256.4410286.4310297.9710308.3510329.1110339.4910349.8710360.96
10370.6310381.0110401.7710412.1510422.5410453.6810464.0610474.4410495.2010505.58
10536.7210547.1110557.4910584.5310619.7710630.1510650.9110671.6810692.4410736.19
10758.4810769.6210791.9010803.0410812.5310825.3210836.4610844.14
   62.28   62.56   62.57   62.69   62.58   62.71   63.21   63.45   64.05   65.09
   65.89   66.80   67.15   67.64   68.85   71.30   71.30   72.76   72.76   74.44
   74.26   73.26   72.75   72.45   72.26   72.35   72.29   72.45   72.98   73.59
   74.32   74.96   75.51   75.91   76.17   77.33   77.49   77.50   78.08   78.20
   78.92   79.37   79.49   80.25   80.56   80.46   80.70   81.20   82.18   82.54
   82.94   83.44   83.89   82.95   81.98   80.41   79.59   80.17
 -937.72 -937.44 -937.43 -937.31 -937.42 -937.29 -936.79 -936.55 -935.95 -934.91
 -934.11 -933.20 -932.85 -932.36 -931.15 -928.70   67.30   68.76 -927.24 -925.56
 -925.74 -926.74 -927.25 -927.55 -927.74 -927.65 -927.71 -927.55 -927.02 -926.41
 -925.68 -925.04 -924.49 -924.09 -923.83 -922.67 -922.51 -922.50 -921.92 -921.80
 -921.08 -920.63 -920.51 -919.75 -919.44 -919.54 -919.30 -918.80 -917.82 -917.46
 -917.06 -916.56 -916.11 -917.05 -918.02 -919.59 -920.41 -919.83
 9293.76 9319.38 9330.00 9340.61 9352.53 9361.85 9383.08 9414.58 9434.59 9464.60
 9484.60 9504.61 9514.61 9524.61 9544.62 9830.00 9830.0010000.0010000.0010196.33
10204.8010235.6810256.4410286.4310297.9710308.3510329.1110339.4910349.8710360.96
10370.6310381.0110401.7710412.1510422.5410453.6810464.0610474.4410495.2010505.58
10536.7210547.1110557.4910584.5310619.7710630.1510650.9110671.6810692.4410736.19
10758.4810769.6210791.9010803.0410812.5310825.3210836.4610844.14
   62.28   62.56   62.57   62.69   62.58   62.71   63.21   63.45   64.05   65.09
   65.89   66.80   67.15   67.64   68.85   71.30   71.30   72.76   72.76   74.44
   74.26   73.26   72.75   72.45   72.26   72.35   72.29   72.45   72.98   73.59
   74.32   74.96   75.51   75.91   76.17   77.33   77.49   77.50   78.08   78.20
   78.92   79.37   79.49   80.25   80.56   80.46   80.70   81.20   82.18   82.54
   82.94   83.44   83.89   82.95   81.98   80.41   79.59   80.17
 -937.72 -937.44 -937.43 -937.31 -937.42 -937.29 -936.79 -936.55 -935.95 -934.91
 -934.11 -933.20 -932.85 -932.36 -931.15 -928.70   67.30   68.76 -927.24 -925.56
 -925.74 -926.74 -927.25 -927.55 -927.74 -927.65 -927.71 -927.55 -927.02 -926.41
 -925.68 -925.04 -924.49 -924.09 -923.83 -922.67 -922.51 -922.50 -921.92 -921.80
 -921.08 -920.63 -920.51 -919.75 -919.44 -919.54 -919.30 -918.80 -917.82 -917.46
 -917.06 -916.56 -916.11 -917.05 -918.02 -919.59 -920.41 -919.83
Pier Skew, UpSta & Num, DnSta & Num=  ,9849.75, 2 ,9849.75, 2 , 0 , 0 , 0 ,,
    4.00    4.00
 -928.53   71.47
    4.00    4.00
 -928.53   71.47
Pier Skew, UpSta & Num, DnSta & Num=  ,9871.50, 2 ,9871.50, 2 , 0 , 0 , 0 ,,
    4.00    4.00
 -928.35   71.65
    4.00    4.00
 -928.35   71.65
Pier Skew, UpSta & Num, DnSta & Num=  ,9893.25, 2 ,9893.25, 2 , 0 , 0 , 0 ,,
    4.00    4.00
 -928.16   71.84
    4.00    4.00
 -928.16   71.84
Pier Skew, UpSta & Num, DnSta & Num=  ,9915.00, 2 ,9915.00, 2 , 0 , 0 , 0 ,,
    4.00    4.00
 -927.97   72.03
    4.00    4.00
 -927.97   72.03
Pier Skew, UpSta & Num, DnSta & Num=  ,9936.75, 2 ,9936.75, 2 , 0 , 0 , 0 ,,
    4.00    4.00
 -927.79   72.21
    4.00    4.00
 -927.79   72.21
Pier Skew, UpSta & Num, DnSta & Num=  ,9958.50, 2 ,9958.50, 2 , 0 , 0 , 0 ,,
    4.00    4.00
 -927.60   72.40
    4.00    4.00
 -927.60   72.40
Pier Skew, UpSta & Num, DnSta & Num=  ,9980.25, 2 ,9980.25, 2 , 0 , 0 , 0 ,,
    4.00    4.00
 -927.41   72.59
    4.00    4.00
 -927.41   72.59
BR Coef=-1 , 0 , 0 ,, 0 ,,,0.8,0,1,0,
WSPro=,,,, 1 ,,,, 0 ,,,, 0 ,,,,-1 ,-1 ,-1 , 0 , 0 , 0 , 0 , 0
BC Design=,, 0 ,, 0 ,,,,,,

Type RM Length L Ch R = 1 ,16425.32,1479.555600,1479.555600,1479.555600
XS GIS Cut Line= 6
 708362.22736755712197.258208588707674.396360368713404.302025467
707463.655302823713864.416722611707218.054644316714491.675379395
707207.858926535715424.583551288706964.868275851716011.760766506
#Sta/Elev= 30
6711.60688.77411 6765.9687.911166822.88563.455746857.46459.480757358.08260.81137
7439.57763.505767497.78960.885367567.64265.806637579.28562.478557774.46259.96056
8045.87462.424588145.41157.13496 8246.7261.180258672.64561.276148887.25164.68547
8908.55658.978178940.37563.845219344.72261.730799544.734 65.93159564.73563.39361
9714.74456.952229874.753 55.78849954.758 45.68799974.75946.4987810004.7642.68124
10024.7647.6951410054.7664.0253510247.2869.6565310290.5776.6260410849.8383.96092
#Mann= 3 , 0 , 0
6711.606  0.0406       06711.606  0.0406       010849.83  0.0406       0
#XS Ineff= 2 , 0
       07074.802                       0
Bank Sta=6711.606,10849.83
Exp/Cntr=0.3,0.1

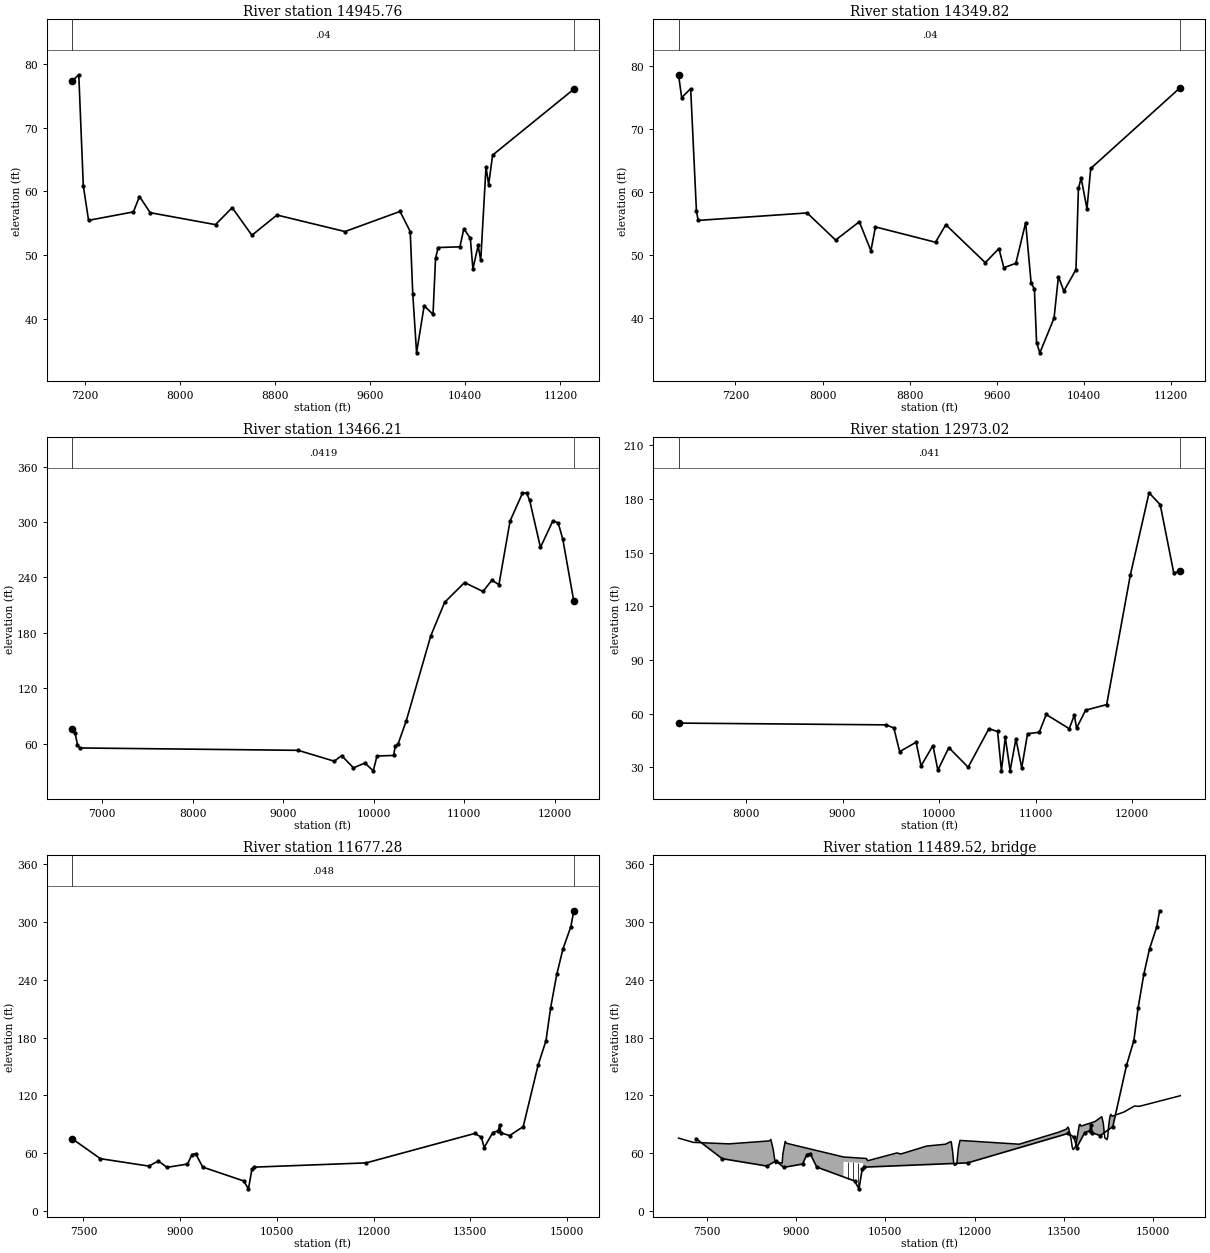
Type RM Length L Ch R = 1 ,14945.76,595.937300,595.937300,595.937300
XS GIS Cut Line= 6
707810.410346551712020.484553351707319.534603095712634.601884881
706358.658983223713766.161258693706176.491439975714083.285981017
705794.208916702714994.702381039705506.417531628715515.523209231
#Sta/Elev= 30
7091.96977.318717148.45478.30177 7186.5260.865497230.72555.427437607.97956.75519
 7659.1859.172417749.34956.632698298.69954.751618438.84257.424258604.91753.08156
8815.57256.264529388.03353.665599851.10656.829229936.85353.661279958.19143.90833
9990.19834.6074710054.0842.0039710128.5940.6541310149.8749.4350810171.3751.15404
10354.9751.2645910387.7554.1052310442.3952.6284510464.25 47.794410508.0951.48216
10530.02 49.1328 10574.463.8426610596.5961.0170510629.8765.6813911313.4776.04642
#Mann= 3 , 0 , 0
7091.969    0.04       07091.969    0.04       011313.47    0.04       0
#XS Ineff= 2 , 0
       07740.275                       0
Bank Sta=7091.969,11313.47
Exp/Cntr=0.3,0.1

Type RM Length L Ch R = 1 ,14349.82,883.618400,883.618400,883.618400
XS GIS Cut Line= 5
707748.099654734711954.157891139706070.321876913713720.824557796
705509.210765839714020.824557781705470.321876913714587.491224468
705031.432988018715448.602335557
#Sta/Elev= 30
6677.74578.635966706.48875.009596789.23476.425466841.98456.990256858.18955.47968
7858.49556.667738119.88452.352578337.70855.268188444.14850.65835 8485.5254.44398
9037.15852.00883 9131.5254.796219494.38648.759749619.121 51.00629664.47947.96289
9774.65348.658789864.865 55.12499914.98245.514719945.05344.58599  9965.136.04969
 9995.1734.4231810125.4839.9434310165.5746.5329310215.6944.2503510326.8547.65612
 10349.360.5785810374.1862.1987810427.8657.3472810462.2763.7357111284.9376.60772
#Mann= 3 , 0 , 0
6677.745    0.04       06677.745    0.04       011284.93    0.04       0
#XS Ineff= 2 , 0
       0 7451.84                       0
Bank Sta=6677.745,11284.93
Exp/Cntr=0.3,0.1

Type RM Length L Ch R = 1 ,13466.21,493.185200,493.185200,493.185200
XS GIS Cut Line= 6
707584.210765839712000.338446677706599.136407316713026.711335436
705568.337583303713757.710141629705270.597521901713842.670221105
704214.432346225713764.249781072702899.637749225714401.560482398
#Sta/Elev= 30
6666.32775.513746699.34372.005576726.11858.780966752.89355.476739163.97552.91091
9564.03241.130269644.76247.203999776.02733.903379901.574 39.17659994.93230.70951
10035.6546.7620510218.4147.3595310238.5257.4722810268.67 59.749510358.7684.67433
 10630.2176.8443 10783.5213.087611003.08 234.47111207.21224.806911305.67237.0324
11383.25232.133611506.43301.1063 11642.7331.046311688.36331.6074 11723.1323.3319
11841.96272.4844 11979.4301.243112038.16298.989612088.63281.561712211.25213.9679
#Mann= 3 , 0 , 0
6666.327  0.0419       06666.327  0.0419       012211.25  0.0419       0
#XS Ineff= 2 , 0
       0 7348.78        10402.67       0
Bank Sta=6666.327,12211.25
Exp/Cntr=0.3,0.1

Type RM Length L Ch R = 1 ,12973.02,1295.745400,1295.745400,1295.745400
XS GIS Cut Line= 6
707454.733926505712112.083551288706541.849967003712972.530691639
705917.293594241713374.529307365705553.600793213 713440.61442396
704288.229937345713258.225117043702886.899770111713863.068294168
#Sta/Elev= 30
7299.26154.667379449.51853.678459531.011  51.9819591.25738.697189762.10743.98198
9813.144  30.7399936.55842.098799987.61128.34242 10101.140.9509710301.5429.96545
10516.1151.47472 10606.549.9802210646.5127.9558710686.5246.6753610736.5428.03826
10796.6345.8145410856.8529.6052510917.2648.7247511038.8349.52842 11110.459.47745
11349.3951.5271811402.1359.1067211425.3751.8642911519.4861.9219611737.2864.98973
11982.99137.563312176.85183.508812292.53176.847512432.56138.722612500.91139.5875
#Mann= 3 , 0 , 0
7299.261   0.041       07299.261   0.041       012500.91   0.041       0
#XS Ineff= 2 , 0
       07864.155        10664.27       0
Bank Sta=7299.261,12500.91
Exp/Cntr=0.3,0.1

Type RM Length L Ch R = 1 ,11677.28,346.395900,346.395900,346.395900
XS GIS Cut Line= 6
707533.023888499  711985.9901447706281.063979864711967.051287085
704586.619535446712317.051287085702797.730646551713483.717953786
701603.286202133  714867.0512871700925.508424342715328.162398234
#Sta/Elev= 30
7323.41474.948257762.08654.156118512.48146.457778663.417 51.72878794.80845.11874
9113.58748.553929182.49858.215419239.515 59.41339350.69245.387949985.12231.00631
10059.8822.7982510113.2843.1159110145.32 45.349511884.9649.7565313572.8180.40829
13671.5576.3752613716.46 65.758913851.1881.2988513935.66 83.158413955.9689.01884
13975.9881.0473714110.3778.1183914322.04 87.449314551.84151.0705 14675.3176.8396
14746.41210.572914842.12245.612314938.88272.198315059.83295.047915107.59311.7665
#Mann= 3 , 0 , 0
7323.414   0.048       07323.414   0.048       015107.59   0.048       0
#XS Ineff= 2 , 0
       09281.781        10149.18       0
Bank Sta=7323.414,15107.59
Exp/Cntr=0.3,0.1

Type RM Length L Ch R = 3 ,11489.52,,,
BEGIN DESCRIPTION:
END DESCRIPTION:
Bridge Culvert--1,0,-1,-1, 0
Deck Dist Width WeirC Skew NumUp NumDn MinLoCord MaxHiCord MaxSubmerge Is_Ogee
117.259700,111.876500,2.6,0, 60, 60, , , 0.95, 0, 0,0,,
 7029.51 7278.76 7879.23 8560.03 8580.04 8620.10 8650.14 8660.16 8700.22 8770.32
 8780.33 8820.39 8840.42 9800.50 9800.5010128.5810128.5810185.1810204.7510696.82
10762.6011195.7511510.2611604.2411611.7111635.1911651.0211664.1311697.0711703.45
11729.6611755.8712749.9313408.1213538.3413568.3213582.9413597.5613620.5913641.42
13656.0413699.9113757.6613771.3713787.6314021.5714137.0514162.2014187.3414225.06
14237.6314250.2014259.7214276.2214287.9214309.2214507.2314688.5614764.6815455.76
   75.53   71.09   69.55   72.63   74.16   63.43   50.72   48.99   50.45   49.49
   58.52   72.09   70.19   55.91   55.91   54.56   54.56   54.33   51.99   60.13
   59.00   67.26   69.17   71.97   70.62   59.99   48.77   47.25   48.09   49.66
   65.42   73.13   69.20   81.59   84.72   86.98   85.32   79.86   74.66   65.78
   63.59   67.26   88.99   89.86   88.02   92.71   97.77   90.92   75.84   73.95
   77.38   86.99   92.15   98.42  100.20   98.26  102.58  108.89  108.49  119.58
 -924.47 -928.91 -930.45 -927.37 -925.84 -936.57 -949.28 -951.01 -949.55 -950.51
 -941.48 -927.91 -929.81 -944.09   50.91   49.56 -945.44 -945.67 -948.01 -939.87
 -941.00 -932.74 -930.83 -928.03 -929.38 -940.01 -951.23 -952.75 -951.91 -950.34
 -934.58 -926.87 -930.80 -918.41 -915.28 -913.02 -914.68 -920.14 -925.34 -934.22
 -936.41 -932.74 -911.01 -910.14 -911.98 -907.29 -902.23 -909.08 -924.16 -926.05
 -922.62 -913.01 -907.85 -901.58 -899.80 -901.74 -897.42 -891.11 -891.51 -880.42
 7029.51 7278.76 7879.23 8560.03 8580.04 8620.10 8650.14 8660.16 8700.22 8770.32
 8780.33 8820.39 8840.42 9820.15 9820.1510148.2310148.2310185.1810204.7510696.82
10762.6011195.7511510.2611604.2411611.7111635.1911651.0211664.1311697.0711703.45
11729.6611755.8712749.9313408.1213538.3413568.3213582.9413597.5613620.5913641.42
13656.0413699.9113757.6613771.3713787.6314021.5714137.0514162.2014187.3414225.06
14237.6314250.2014259.7214276.2214287.9214309.2214507.2314688.5614764.6815455.76
   75.53   71.09   69.55   72.63   74.16   63.43   50.72   48.99   50.45   49.49
   58.52   72.09   70.19   55.83   55.83   54.48   54.48   54.33   51.99   60.13
   59.00   67.26   69.17   71.97   70.62   59.99   48.77   47.25   48.09   49.66
   65.42   73.13   69.20   81.59   84.72   86.98   85.32   79.86   74.66   65.78
   63.59   67.26   88.99   89.86   88.02   92.71   97.77   90.92   75.84   73.95
   77.38   86.99   92.15   98.42  100.20   98.26  102.58  108.89  108.49  119.58
 -924.47 -928.91 -930.45 -927.37 -925.84 -936.57 -949.28 -951.01 -949.55 -950.51
 -941.48 -927.91 -929.81 -944.17   50.83   49.48 -945.52 -945.67 -948.01 -939.87
 -941.00 -932.74 -930.83 -928.03 -929.38 -940.01 -951.23 -952.75 -951.91 -950.34
 -934.58 -926.87 -930.80 -918.41 -915.28 -913.02 -914.68 -920.14 -925.34 -934.22
 -936.41 -932.74 -911.01 -910.14 -911.98 -907.29 -902.23 -909.08 -924.16 -926.05
 -922.62 -913.01 -907.85 -901.58 -899.80 -901.74 -897.42 -891.11 -891.51 -880.42
Pier Skew, UpSta & Num, DnSta & Num=  ,9881.52, 2 ,9901.17, 2 , 0 , 0 , 0 ,,
    4.00    4.00
 -944.42   55.58
    4.00    4.00
 -944.50   55.50
Pier Skew, UpSta & Num, DnSta & Num=  ,9964.54, 2 ,9984.19, 2 , 0 , 0 , 0 ,,
    4.00    4.00
 -944.76   55.24
    4.00    4.00
 -944.84   55.16
Pier Skew, UpSta & Num, DnSta & Num=  ,10047.56, 2 ,10067.21, 2 , 0 , 0 , 0 ,,
    4.00    4.00
 -945.10   54.90
    4.00    4.00
 -945.18   54.82
BR Coef=-1 , 0 , 0 ,, 0 ,,,0.8,0,1,0,
WSPro=,,,, 1 ,,,, 0 ,,,, 0 ,,,,-1 ,-1 ,-1 , 0 , 0 , 0 , 0 , 0
BC Design=,, 0 ,, 0 ,,,,,,

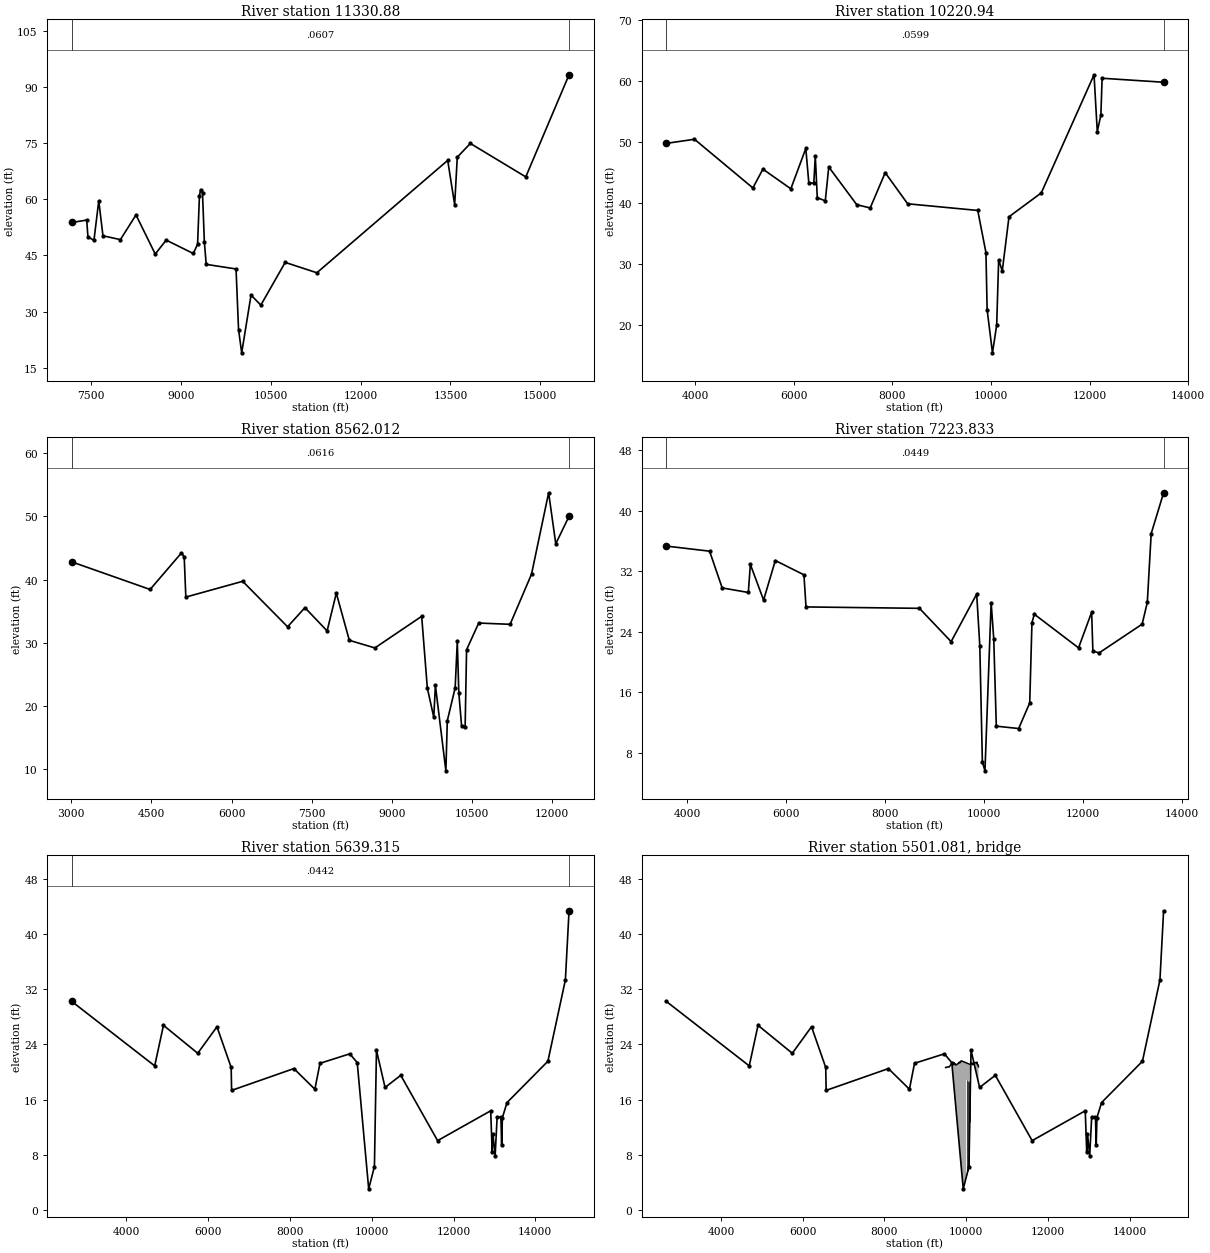
Type RM Length L Ch R = 1 ,11330.88,1109.937800,1109.937800,1109.937800
XS GIS Cut Line= 6
707521.400593162711696.458551303706035.369535446711553.162398189
703796.480646521712247.606842652703079.813979864712714.273509309
700974.258424342714719.829064861700285.369535416714847.606842652
#Sta/Elev= 30
7173.84453.778157422.52554.41774 7442.7149.948777543.29848.999737623.59459.57748
7693.85350.222847984.92549.200258245.887 55.79148567.07145.34424 8749.7849.07191
9202.59445.496519274.63347.945719305.50660.916119326.08962.554499356.96361.61733
9387.83648.60152 9418.7142.586879917.14841.365439959.18425.1495910011.7318.96368
10167.4734.3854710331.5931.7099210738.3943.1173311267.5140.3463213453.43 70.3565
13569.7258.5332813613.3371.2076113831.3874.8862314757.67 65.949615480.7593.21941
#Mann= 3 , 0 , 0
7173.844  0.0607       07173.844  0.0607       015480.75  0.0607       0
#XS Ineff= 2 , 0
       09789.542         10198.4       0
Bank Sta=7173.844,15480.75
Exp/Cntr=0.3,0.1

Type RM Length L Ch R = 1 ,10220.94,1658.929600,1658.929600,1658.929600
XS GIS Cut Line= 5
  710017.6536614709821.582018986704436.036553919710687.046982035
703727.703220576711457.880315349702852.703220576712270.380315349
701116.665999055  713604.0248034
#Sta/Elev= 30
3421.18649.750593990.56450.423735174.54542.436775376.93545.524415943.62742.30209
6247.21248.915326307.92943.277426409.12443.216536439.48247.65019 6479.9640.82793
6641.87240.334326712.70945.87465  7279.439.698327552.62739.163297856.21244.94431
8311.58939.844059732.18738.752659898.67131.84084 9922.3222.4804810030.9715.40994
10116.3619.9712610156.2230.6651310229.2228.8199210365.6937.7176111020.7241.63439
12089.5160.9936112155.1751.6908912228.07 54.380712253.2960.4239913499.59 59.7715
#Mann= 3 , 0 , 0
3421.186  0.0599       03421.186  0.0599       013499.59  0.0599       0
#XS Ineff= 2 , 0
       08870.496         10377.8       0
Bank Sta=3421.186,13499.59
Exp/Cntr=0.3,0.1

Type RM Length L Ch R = 1 ,8562.012,1338.179100,1338.179100,1338.179100
XS GIS Cut Line= 4
709290.657133609708747.363268986704169.129355818709561.165352315
703094.910605818709864.984796777701109.233522505712111.078546777
#Sta/Elev= 30
3013.108 42.78714476.90238.420365064.17944.220655114.80643.584425145.18237.21644
6208.35539.714147048.76832.511977372.78335.541677787.92631.857167960.05937.83921
 8203.1830.369218681.22529.161469556.67934.169689662.30122.810739783.14918.17039
9813.345 23.218110009.349.69459910036.0317.6331710182.8522.83443 10222.930.19987
10251.1922.0895510302.9816.7925210369.7216.7110910396.4128.8754810623.3233.10406
11210.6132.9029411611.0440.8409411931.3853.7366612064.8545.6575212313.2250.01622
#Mann= 3 , 0 , 0
3013.108  0.0616       03013.108  0.0616       012313.22  0.0616       0
#XS Ineff= 2 , 0
       08543.591                       0
Bank Sta=3013.108,12313.22
Exp/Cntr=0.3,0.1

Type RM Length L Ch R = 1 ,7223.833,1584.518100,1584.518100,1584.518100
XS GIS Cut Line= 6
708433.452272505707683.995213419706686.490466923 707998.66535233
701654.642635465709307.420819402701162.229774833709710.925802365
700245.794728756710907.762616292 699828.61161074711728.450717226
#Sta/Elev= 30
 3586.3535.311754458.617 34.6381 4712.6429.789055241.00829.185385281.65232.89129
5548.69628.185685786.02133.405666363.857  31.5176405.13127.278898695.83827.09349
9335.58522.697299851.81928.972339914.37322.182379966.5016.82499810018.63  5.6406
10143.7427.8515510195.8723.0882310247.99 11.540110699.3111.2256410922.68 14.6094
10967.5325.1962411014.86  26.317 11908.221.87465 12172.726.5766112197.8921.44389
12323.84 21.211313192.4125.0045513296.6127.8703813375.1436.96258 13625.842.34837
#Mann= 3 , 0 , 0
 3586.35  0.0449       0 3586.35  0.0449       0 13625.8  0.0449       0
#XS Ineff= 2 , 0
       09758.784                       0
Bank Sta=3586.35,13625.8
Exp/Cntr=0.3,0.1

Type RM Length L Ch R = 1 ,5639.315,284.880600,284.880600,284.880600
XS GIS Cut Line= 6
708298.081617087706891.488915771707179.290352941706979.861024931
700326.076197982708366.087918997699451.076197982709095.254585624
698440.659531295710584.837918967698042.443500876711578.237048715
#Sta/Elev= 30
2667.50730.228114693.38620.881314907.97226.769435745.88122.710256215.92826.56109
6563.35320.651686573.57217.323598096.11320.488778609.89317.492478734.946  21.256
 9464.4222.63083 9645.6721.352489925.8573.03423210065.956.26555510115.9823.14472
10326.1217.7484510709.8819.5141611610.6810.0303412909.0214.3629312945.27 8.35984
12963.1311.0394413017.777.84868613066.11 13.418313159.0813.41904 13176.99.366247
13194.7113.3604713307.78 15.5517 14307.421.5518314735.2433.3555214824.9243.39457
#Mann= 3 , 0 , 0
2667.507  0.0442       02667.507  0.0442       014824.92  0.0442       0
#XS Ineff= 2 , 0
       09198.967        13353.36       0
Bank Sta=2667.507,14824.92
Exp/Cntr=0.3,0.1

Type RM Length L Ch R = 3 ,5501.081,,,
BEGIN DESCRIPTION:
END DESCRIPTION:
Bridge Culvert--1,0,-1,-1, 0
Deck Dist Width WeirC Skew NumUp NumDn MinLoCord MaxHiCord MaxSubmerge Is_Ogee
129.809100,25.262400,2.6,0, 33, 34, , , 0.95, 0, 0,0,,
 9496.25 9499.57 9559.62 9579.63 9631.00 9660.23 9670.43 9690.82 9701.02 9721.41
 9731.61 9752.00 9813.17 9825.89 9843.76 9864.15 9874.35 9884.55 9997.45 9997.45
10112.1010133.3410159.8410172.4510172.4510190.9110206.7110247.5910258.9310270.26
10281.6010292.9410298.97
   20.66   20.61   20.77   20.70   21.14   21.14   21.06   21.31   21.35   21.05
   21.16   21.02   21.28   21.42   21.32   21.56   21.53   21.60   21.33   21.33
   21.05   21.35   21.04   21.18   21.18   21.15   21.39   21.31   21.43   21.08
   21.08   20.93   20.75
 -979.34 -979.39 -979.23 -979.30 -978.86 -978.86 -978.94 -978.69 -978.65 -978.95
 -978.84 -978.98 -978.72 -978.58 -978.68 -978.44 -978.47 -978.40 -978.67   18.83
   18.55   18.85   18.54   18.68 -978.82 -978.85 -978.61 -978.69 -978.57 -978.92
 -978.92 -979.07 -979.25
 9496.25 9499.57 9559.62 9579.63 9631.00 9660.23 9670.43 9690.82 9701.02 9721.41
 9731.61 9752.00 9813.17 9825.89 9843.76 9864.15 9874.35 9884.55 9917.81 9917.81
10092.8110092.8110112.1010133.3410159.8410170.0410190.9110206.7110247.5910258.93
10270.2610281.6010292.9410298.97
   20.66   20.61   20.77   20.70   21.14   21.14   21.06   21.31   21.35   21.05
   21.16   21.02   21.28   21.42   21.32   21.56   21.53   21.60   21.52   21.52
   21.10   21.10   21.05   21.35   21.04   21.17   21.15   21.39   21.31   21.43
   21.08   21.08   20.93   20.75
 -979.34 -979.39 -979.23 -979.30 -978.86 -978.86 -978.94 -978.69 -978.65 -978.95
 -978.84 -978.98 -978.72 -978.58 -978.68 -978.44 -978.47 -978.40 -978.48   19.02
   18.60 -978.90 -978.95 -978.65 -978.96 -978.83 -978.85 -978.61 -978.69 -978.57
 -978.92 -978.92 -979.07 -979.25
Pier Skew, UpSta & Num, DnSta & Num=  ,10018.20, 2 ,9938.56, 2 , 0 , 0 , 0 ,,
    3.00    3.00
 -978.72   21.28
    3.00    3.00
 -978.53   21.47
Pier Skew, UpSta & Num, DnSta & Num=  ,10040.45, 2 ,9960.81, 2 , 0 , 0 , 0 ,,
    3.00    3.00
 -978.78   21.22
    3.00    3.00
 -978.58   21.42
Pier Skew, UpSta & Num, DnSta & Num=  ,10062.70, 2 ,9983.06, 2 , 0 , 0 , 0 ,,
    3.00    3.00
 -978.83   21.17
    3.00    3.00
 -978.64   21.36
Pier Skew, UpSta & Num, DnSta & Num=  ,10084.95, 2 ,10005.31, 2 , 0 , 0 , 0 ,,
    3.00    3.00
 -978.88   21.12
    3.00    3.00
 -978.69   21.31
Pier Skew, UpSta & Num, DnSta & Num=  ,10107.20, 2 ,10027.56, 2 , 0 , 0 , 0 ,,
    3.00    3.00
 -978.94   21.06
    3.00    3.00
 -978.74   21.26
Pier Skew, UpSta & Num, DnSta & Num=  ,10129.45, 2 ,10049.81, 2 , 0 , 0 , 0 ,,
    3.00    3.00
 -978.67   21.33
    3.00    3.00
 -978.80   21.20
Pier Skew, UpSta & Num, DnSta & Num=  ,10151.70, 2 ,10072.06, 2 , 0 , 0 , 0 ,,
    3.00    3.00
 -978.86   21.14
    3.00    3.00
 -978.85   21.15
BR Coef=-1 , 0 , 0 ,, 0 ,,,0.8,0,1,0,
WSPro=,,,, 1 ,,,, 0 ,,,, 0 ,,,,-1 ,-1 ,-1 , 0 , 0 , 0 , 0 , 0
BC Design=,, 0 ,, 0 ,,,,,,

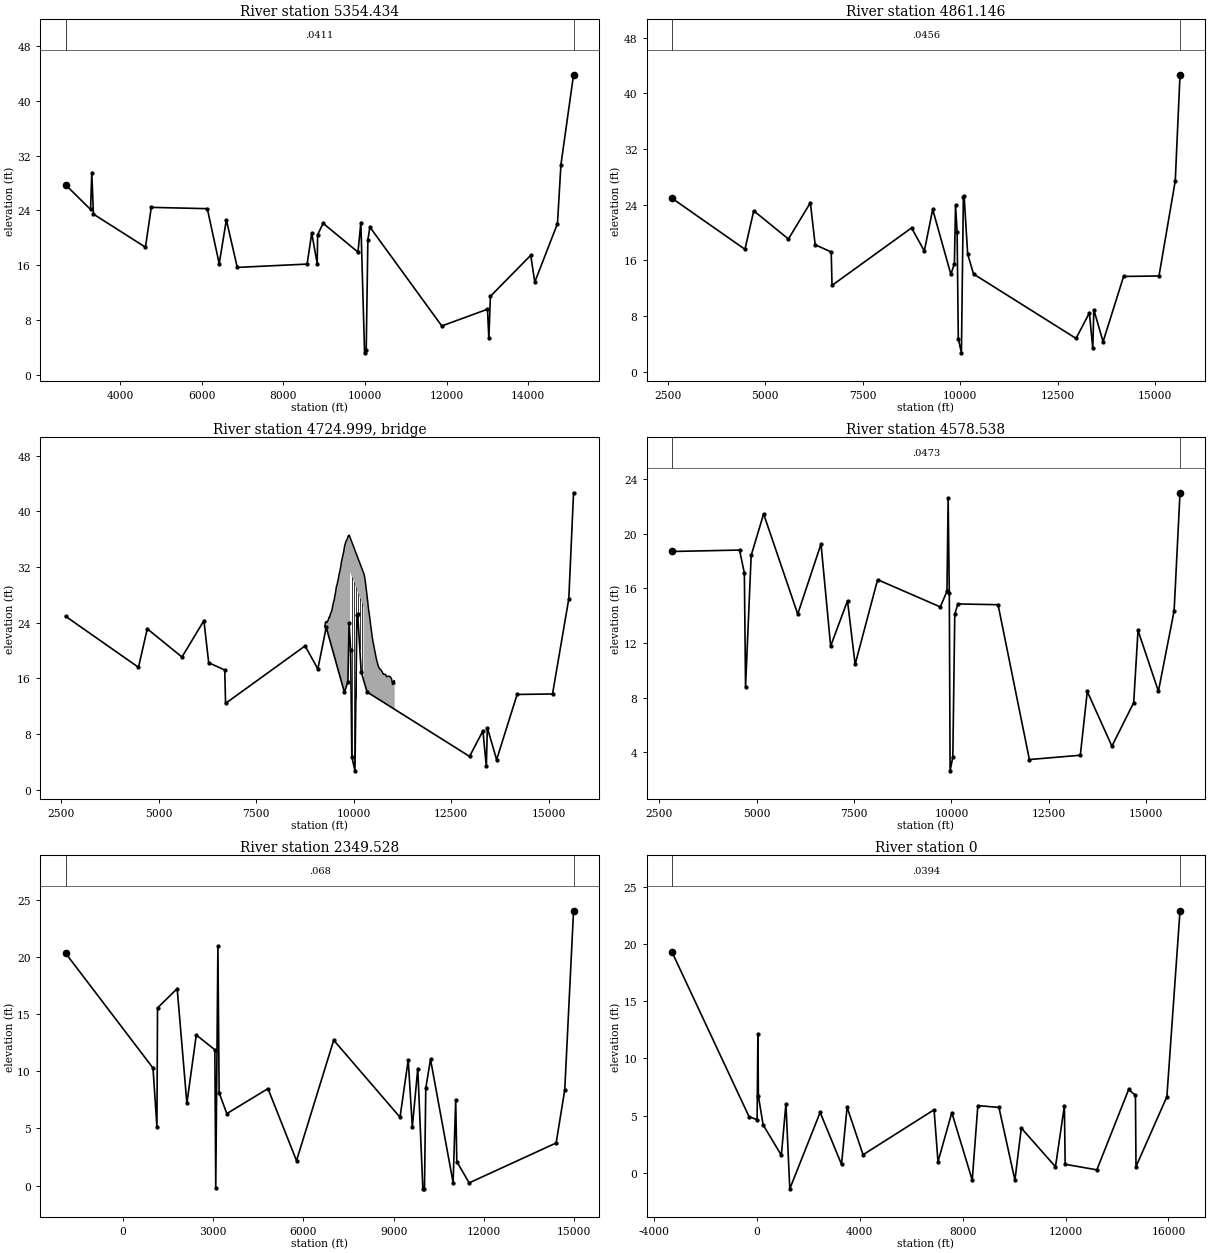
Type RM Length L Ch R = 1 ,5354.434,493.288800,493.288800,493.288800
XS GIS Cut Line= 6
708194.868549436706691.513597175701621.486302078708026.832660213
700315.659531265708043.171252295699159.409531295708886.921252295
698159.409531355 710449.42125231697797.881223112711507.552886128
#Sta/Elev= 30
2661.35927.746143275.08324.131623305.27229.504183345.525   23.464619.94918.63291
4762.61524.443176135.458 24.25116427.10616.228396602.27622.614986870.18115.68452
8580.65716.170958694.00220.686028827.95516.237828838.25920.438148972.21222.12037
9826.77517.916479897.39522.230339988.1913.22757910028.553.626446 10068.919.73061
10119.3421.5610311880.247.14869312999.179.58372713033.385.33144413070.4811.46867
14059.15  17.45414158.1413.5441214714.34 22.072814798.8830.6689115108.0443.77602
#Mann= 3 , 0 , 0
2661.359  0.0411       02661.359  0.0411       015108.04  0.0411       0
#XS Ineff= 2 , 0
       09184.109        13433.78       0
Bank Sta=2661.359,15108.04
Exp/Cntr=0.3,0.1

Type RM Length L Ch R = 1 ,4861.146,282.607100,282.607100,282.607100
XS GIS Cut Line= 6
708040.487182766706341.346436873701510.845491111707770.288641006
701281.305451393707485.707136735700072.968319237707578.429937139
698348.959905773709344.693458781697520.759785593711432.095802531
#Sta/Elev= 30
2608.09324.94279 4479.4617.603644704.48323.137525594.35119.08174 6156.91 24.3037
 6279.65 18.25816691.47117.219546712.18112.41804 8751.5920.680769078.91617.36079
9293.72323.337179759.53514.008529849.67415.53045 9879.7223.939379919.782 20.0936
9949.8284.75564710029.952.72261810080.0325.1344310100.0625.23474 10190.216.93214
10340.7614.0531612969.424.79390713311.078.46137813398.79 3.3713113425.168.928043
13662.454.32125614188.4413.7021515096.27 13.769515513.7827.4580115635.3842.68844
#Mann= 3 , 0 , 0
2608.093  0.0456       02608.093  0.0456       015635.38  0.0456       0
#XS Ineff= 2 , 0
       09122.189        13733.68       0
Bank Sta=2608.093,15635.38
Exp/Cntr=0.3,0.1

Type RM Length L Ch R = 3 ,4724.999,,,
BEGIN DESCRIPTION:
END DESCRIPTION:
Bridge Culvert--1,0,-1,-1, 0
Deck Dist Width WeirC Skew NumUp NumDn MinLoCord MaxHiCord MaxSubmerge Is_Ogee
113.303550,56.000000,2.6,0, 60, 60, , , 0.95, 0, 0,0,,
 9254.19 9261.91 9273.47 9296.59 9308.15 9319.71 9349.88 9365.94 9377.50 9409.70
 9429.64 9483.55 9498.44 9512.32 9526.83 9555.69 9572.54 9590.38 9601.13 9611.88
 9665.65 9676.77 9686.61 9736.85 9766.99 9797.13 9837.32 9857.41 9882.65 9904.20
 9904.2010252.7510252.7510270.7010299.4810339.6710349.7110359.7610369.8110379.85
10399.9510430.0910480.3210570.8010590.9210625.7210651.2710701.5610761.9010812.51
10842.3710905.9010953.0010973.1210993.2311013.3511023.4111033.4611043.5211049.20
   23.50   23.63   24.11   24.18   24.02   24.11   24.49   24.80   24.77   25.41
   25.59   27.08   27.27   27.80   28.19   29.25   29.50   30.03   30.23   30.62
   32.05   32.55   32.85   34.10   35.10   35.65   36.12   36.48   36.60   36.28
   36.28   31.15   31.15   30.88   29.79   27.93   27.39   27.01   26.37   25.91
   25.17   23.80   21.68   19.05   18.55   17.84   17.48   17.20   16.60   16.59
   16.26   16.34   16.12   15.85   15.13   15.21   15.59   15.70   15.56   15.24
 -976.50 -976.37 -975.89 -975.82 -975.98 -975.89 -975.51 -975.20 -975.23 -974.59
 -974.41 -972.92 -972.73 -972.20 -971.81 -970.75 -970.50 -969.97 -969.77 -969.38
 -967.95 -967.45 -967.15 -965.90 -964.90 -964.35 -963.88 -963.52 -963.40 -963.72
   31.28   26.15 -968.85 -969.12 -970.21 -972.07 -972.61 -972.99 -973.63 -974.09
 -974.83 -976.20 -978.32 -980.95 -981.45 -982.16 -982.52 -982.80 -983.40 -983.41
 -983.74 -983.66 -983.88 -984.15 -984.87 -984.79 -984.41 -984.30 -984.44 -984.76
 9254.19 9261.91 9270.12 9273.47 9296.59 9308.15 9319.71 9349.88 9365.94 9377.50
 9409.70 9429.64 9483.55 9498.44 9512.32 9526.83 9555.69 9572.54 9590.38 9601.13
 9611.88 9665.65 9676.77 9686.61 9736.85 9766.99 9797.13 9837.32 9847.36 9877.50
 9882.65 9923.41 9923.4110271.9610271.9610309.5210349.7110359.7610369.8110379.85
10399.9510430.0910480.3210570.8010590.9210625.7210651.2710701.5610761.9010812.51
10842.3710905.9010953.0010973.1210993.2311013.3511023.4111033.4611043.5211049.20
   23.50   23.63   24.03   24.11   24.18   24.02   24.11   24.49   24.80   24.77
   25.41   25.59   27.08   27.27   27.80   28.19   29.25   29.50   30.03   30.23
   30.62   32.05   32.55   32.85   34.10   35.10   35.65   36.12   36.36   36.61
   36.60   36.00   36.00   30.84   30.84   29.37   27.39   27.01   26.37   25.91
   25.17   23.80   21.68   19.05   18.55   17.84   17.48   17.20   16.60   16.59
   16.26   16.34   16.12   15.85   15.13   15.21   15.59   15.70   15.56   15.24
 -976.50 -976.37 -975.97 -975.89 -975.82 -975.98 -975.89 -975.51 -975.20 -975.23
 -974.59 -974.41 -972.92 -972.73 -972.20 -971.81 -970.75 -970.50 -969.97 -969.77
 -969.38 -967.95 -967.45 -967.15 -965.90 -964.90 -964.35 -963.88 -963.64 -963.39
 -963.40 -964.00   31.00   25.84 -969.16 -970.63 -972.61 -972.99 -973.63 -974.09
 -974.83 -976.20 -978.32 -980.95 -981.45 -982.16 -982.52 -982.80 -983.40 -983.41
 -983.74 -983.66 -983.88 -984.15 -984.87 -984.79 -984.41 -984.30 -984.44 -984.76
Pier Skew, UpSta & Num, DnSta & Num=  ,9952.56, 2 ,9971.78, 2 , 0 , 0 , 0 ,,
    4.00    4.00
 -964.43   35.57
    4.00    4.00
 -964.71   35.29
Pier Skew, UpSta & Num, DnSta & Num=  ,10002.92, 2 ,10022.14, 2 , 0 , 0 , 0 ,,
    4.00    4.00
 -965.17   34.83
    4.00    4.00
 -965.45   34.55
Pier Skew, UpSta & Num, DnSta & Num=  ,10053.29, 2 ,10072.50, 2 , 0 , 0 , 0 ,,
    4.00    4.00
 -965.91   34.09
    4.00    4.00
 -966.20   33.80
Pier Skew, UpSta & Num, DnSta & Num=  ,10103.65, 2 ,10122.87, 2 , 0 , 0 , 0 ,,
    4.00    4.00
 -966.66   33.34
    4.00    4.00
 -966.94   33.06
Pier Skew, UpSta & Num, DnSta & Num=  ,10154.02, 2 ,10173.23, 2 , 0 , 0 , 0 ,,
    4.00    4.00
 -967.40   32.60
    4.00    4.00
 -967.68   32.32
Pier Skew, UpSta & Num, DnSta & Num=  ,10204.38, 2 ,10223.60, 2 , 0 , 0 , 0 ,,
    4.00    4.00
 -968.14   31.86
    4.00    4.00
 -968.42   31.58
BR Coef=-1 , 0 , 0 ,, 0 ,,,0.8,0,1,0,
WSPro=,,,, 1 ,,,, 0 ,,,, 0 ,,,,-1 ,-1 ,-1 , 0 , 0 , 0 , 0 , 0
BC Design=,, 0 ,, 0 ,,,,,,

Type RM Length L Ch R = 1 ,4578.538,2229.010100,2229.010100,2229.010100
XS GIS Cut Line= 6
707868.120658547705741.804374769701521.116493553707300.334481254
699719.849048972707281.940467507699340.398177624707591.122659013
697632.869256318710099.714531004697176.122837067 711153.74472931
#Sta/Elev= 30
 2829.5318.689224562.65118.794254686.21617.119224717.1078.7989394861.26618.40032
5180.47621.440086055.72714.108116652.957 19.24046900.086 11.76847332.56315.08261
7528.20810.429818104.84416.626679713.47714.635059884.02515.778269914.12222.57806
9944.21915.631529964.2832.64400510034.513.65727310084.6714.1071810164.9314.85263
11194.7914.7965711998.623.47071913305.073.78541813483.968.44834814115.55 4.44817
14674.677.62912914785.1512.9205115308.288.46283415711.5214.3492215862.7322.98399
#Mann= 3 , 0 , 0
 2829.53  0.0473       0 2829.53  0.0473       015862.73  0.0473       0
#XS Ineff= 2 , 0
       0 9373.72           13945       0
Bank Sta=2829.53,15862.73
Exp/Cntr=0.3,0.1

Type RM Length L Ch R = 1 ,2349.528,2349.528400,2349.528400,2349.528400
XS GIS Cut Line= 6
710608.462472349704696.541585937705859.667550266705086.338963419
700208.625883609706062.901463419698620.084216952707013.422296762
697148.730050296709305.088963449696549.771716952711010.818130091
#Sta/Elev= 30
-1910.4220.31961998.962610.271261129.2275.1085751149.26815.529521802.77417.21115
2125.237 7.180832437.62413.160553054.88311.869023085.508-0.203523156.969 20.9631
3197.8038.1051673453.0186.2861284820.9728.4726595770.3732.1756867007.14512.70771
9212.2145.9703179484.54210.977729621.0915.1281849802.42210.229399971.348-0.28707
10024.74-0.2870710068.378.49841210225.5311.0359410977.590.25596111063.317.515031
11100.052.09258311510.670.23416814403.153.72085614689.318.36665614981.6424.01796
#Mann= 3 , 0 , 0
-1910.42   0.068       0-1910.42   0.068       014981.64   0.068       0
#XS Ineff= 2 , 0
       07750.502        12642.03       0
Bank Sta=-1910.42,14981.64
Exp/Cntr=0.3,0.1

Type RM Length L Ch R = 1 ,       0,0.000000,0.000000,0.000000
XS GIS Cut Line= 6
710532.770343333704595.618747264702593.720229924702838.839481547
 697285.52661854705929.762609228697384.137729645706722.818164811
 696282.26189658708903.075592652695729.143199056710832.073266476
#Sta/Elev= 30
-3300.64 19.3089-304.7264.9029469.2716794.62649339.65856 12.095859.916476.677588
243.82264.184735951.88481.5182131129.7116.0203981280.262-1.417392460.3525.272336
3291.1450.7217063507.8985.7264964128.6691.5663976889.4695.5028987042.156 0.95326
7579.2185.2517348373.361-0.656178591.369 5.868839411.3925.70625510032.51-0.65617
10281.293.90289111609.950.51454811956.265.84812211986.410.73307913217.59 0.24373
14454.927.27752814719.036.76963814740.160.53305915940.896.64348416451.4622.91653
#Mann= 3 , 0 , 0
-3300.64  0.0394       0-3300.64  0.0394       016451.46  0.0394       0
#XS Ineff= 2 , 0
       06910.133        13617.76       0
Bank Sta=-3300.64,16451.46
Exp/Cntr=0.3,0.1